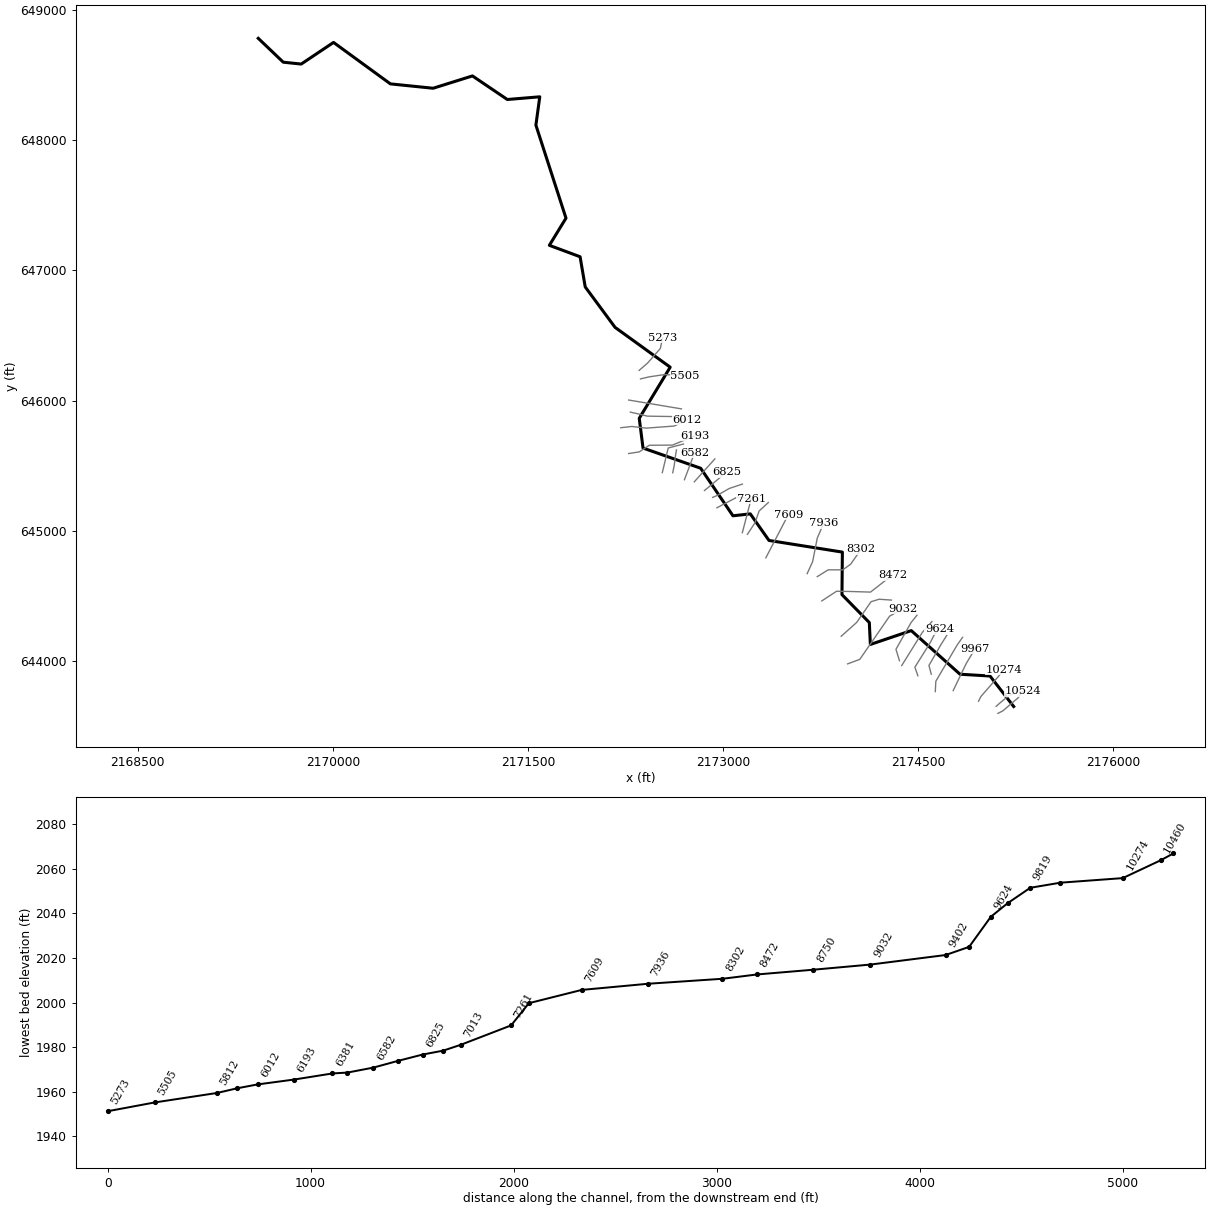
--- GETOUTRN.prj (project) ---

Proj Title=GETOUTRN
Current Plan=p01
Default Exp/Contr=0,0
English Units
Geom File=g01
Flow File=f01
Plan File=p01
BEGIN DESCRIPTION:
---------- MODELED AS PART OF WVEMD CTP PROGRAM, 2023----------
Stream Name: Getout Run
Flood Zone:  AFH
Upshur County, WV
HEC-RAS Version: RAS 6.3
Vertical Datum: NAVD88
Projection: NAD 1983 StatePlane West Virginia S FIPS 4702 (US Feet)
Terrain: 1-meter LIDAR (FEMA Region III 3DEP collected 2016-2018)
Land Use: 2019 NLCD
Hydrologic Method:
WV SIR2010-5033 regression equations
Additional Model Notes:
Coincident peak with LIKANARV
END DESCRIPTION:
DSS File=dss
DSS Export Rating Curves= 0
DSS Export Rating Curve Sorted= 0
DSS Export Volume Flow Curves= 0
DXF OffsetX= 0
DXF OffsetY= 0
DXF ScaleX= 0
DXF ScaleY= 0

--- GETOUTRN.p01 (plan) ---

Plan Title=Floodplain
Program Version=6.30
Short Identifier=Floodplain
Geom File=g01
Flow File=f01
Subcritical Flow
K Sum by GR= 0
Std Step Tol= 0.01
Critical Tol= 0.01
Num of Std Step Trials= 20
Max Error Tol= 0.3
Flow Tol Ratio= 0.001
Split Flow NTrial= 30
Split Flow Tol= 0.02
Split Flow Ratio= 0.02
Log Output Level= 0
Friction Slope Method= 1
Unsteady Friction Slope Method= 2
Unsteady Bridges Friction Slope Method= 1
Parabolic Critical Depth
Global Vel Dist= 0 , 0 , 0
Global Log Level= 0
CheckData=False
Encroach Param=-1 ,0,0, 0
Computation Interval=0.1SEC
Output Interval=1SEC
Instantaneous Interval=Max Profile
Mapping Interval=1HOUR
Computation Time Step Use Courant=        0
Computation Time Step Use Time Series=    0
Computation Time Step Count To Double=0
Computation Time Step Max Doubling=0
Computation Time Step Max Halving=0
Computation Time Step Residence Courant=0
Run HTab= 0
Run UNet= 0
Run Sediment= 0
Run PostProcess= 0
Run WQNet= 0
Run RASMapper=-1
UNET Theta= 0
UNET Theta Warmup= 0
UNET ZTol= 0
UNET ZSATol= 0
UNET MxIter= 0
UNET Max Iter WO Improvement= 0
UNET MaxInSteps= 0
UNET DtIC= 0
UNET DtMin= 0
UNET MaxCRTS= 0
UNET WFStab= 0
UNET SFStab= 0
UNET WFX= 1
UNET SFX= 1
UNET Gravity=32.17405
UNET 1D Methodology=Finite Difference
UNET DSS MLevel= 1
UNET Pardiso=0
UNET DZMax Abort= 0
UNET Use Existing IB Tables= 0
UNET Froude Reduction=False
UNET Froude Limit= 0
UNET Froude Power= 0
UNET D1 Cores= 0
UNET WindReference=Eulerian
UNET WindDragFormulation=Hsu (1988)
UNET D2 Coriolis=0
UNET D2 Cores= 0
UNET D2 Theta= 1
UNET D2 Theta Warmup= 1
UNET D2 Z Tol= 0.01
UNET D2 Volume Tol= 0.01
UNET D2 Max Iterations= 20
UNET D2 Equation= 0
UNET D2 RampUpFraction=0.1
UNET D2 TimeSlices= 1
UNET D2 Turbulence Formulation=Non-Conservative (original)
UNET D2 Eddy Viscosity=0.3
UNET D2 Transverse Eddy Viscosity=0.1
UNET D2 Smagorinsky Mixing=0
UNET D2 BCVolumeCheck=0
UNET D2 Cores=0
UNET D2 SolverType=PARDISO (Direct)
UNET D2 Minimum Iterations= 3
UNET D2 Maximum Iterations= 30
UNET D2 Restart Number= 10
UNET D2 Relaxation Coeff=1.3
UNET D2 SOR Precondition Iterations= 10
UNET D2 ILUT Maximum Fill= 8
UNET D2 ILUT Tolerance=1E-08
UNET D2 Convergence Tolerance=0.00001
UNET D1D2 MaxIter= 0
UNET D1D2 ZTol=0.01
UNET D1D2 QTol=0.1
UNET D1D2 MinQTol=1
DSS File=dss
Write IC File= 0
Write IC File at Fixed DateTime=0
Write IC File at Sim End=0
Echo Input=False
Echo Parameters=False
Echo Output=False
Write Detailed= 0
HDF Write Warmup=0
HDF Write Time Slices=0
HDF Flush=0
HDF Compression= 1
HDF Chunk Size= 1
HDF Spatial Parts= 1
HDF Use Max Rows=0
HDF Fixed Rows= 1
Calibration Method= 0
Calibration Iterations= 20
Calibration Max Change=0.05
Calibration Tolerance=0.2
Calibration Maximum=1.5
Calibration Minimum=0.5
Calibration Optimization Method= 1
WQ AD Non Conservative
WQ ULTIMATE=-1
WQ Max Comp Step=1HOUR
WQ Output Interval=15MIN
WQ Output Selected Increments= 0
WQ Output face flow=0
WQ Output face velocity=0
WQ Output face area=0
WQ Output face dispersion=0
WQ Output cell volume=0
WQ Output cell surface area=0
WQ Output cell continuity=0
WQ Output cumulative cell continuity=0
WQ Output face conc=0
WQ Output face dconc_dx=0
WQ Output face courant=0
WQ Output face peclet=0
WQ Output face adv mass=0
WQ Output face disp mass=0
WQ Output cell mass=0
WQ Output cell source sink temp=0
WQ Output nsm pathways=0
WQ Output nsm derived pathways=0
WQ Create Restart=0
WQ Fixed Restart=0
WQ System Summary=0
WQ Write To DSS=0
Sorting and Armoring Iterations= 10
XS Update Threshold= 0.02
Bed Roughness Predictor= 0
Hydraulics Update Threshold= 0.02
Energy Slope Method= 1
Volume Change Method= 1
Sediment Retention Method= 0
Sediment TS Multiplier= 1
Warm Up Method= 0
XS Weighting Method= 0
Number of US Weighted Cross Sections= 1
Number of DS Weighted Cross Sections= 1
Upstream XS Weight=0
Main XS Weight=1
Downstream XS Weight=0
Number of DS XS's Weighted with US Boundary= 1
Upstream Boundary Weight= 1
Weight of XSs Associated with US Boundary= 0
Number of US XS's Weighted with DS Boundary= 1
Downstream Boundary Weight= 0.5
Weight of XSs Associated with DS Boundary= 0.5
Percentile Method= 0
Sediment Output Level= 3
Mass or Volume Output= 0
Output Increment Type= 1
Profile and TS Output Increment= 1
Transport Output Increment 1
XS Output Flag= 0
XS Output Increment= 10
Read HDF5 Sediment Hotstart= 0
Sediment Hotstart Type= 0
Write Gradation File= 0
Read Gradation Hotstart= 0
Write HDF5 File= 1
Write Binary Output= 1
Write DSS Sediment File= 0
DSS Sediment Output Type= 1
SV Curve= 0
Specific Gage Flag= 0
Subcell Erosion Methods= 0
Subcell Deposition Methods= 0
Advection Scheme= 1
Matrix Solver= 0
Implicit Weighting Factor= 1
Maximum Outer Loop Convergence Iterations= 5
Convergence Maximum Absolute= 0.001
Convergence RMSE= 0.0001
Grain Fractions Max Abs Error= 0.001
Max Subgrid Regions= 1
Max Subgrid Length Scale= 3.402823E+38
Initial Layer Thickness= 3.402823E+38
Min Layer Thickness= 3.402823E+38
Max Layer Thickness= 3.402823E+38
Number of Layers= 5

--- GETOUTRN.f01 (steady flow) ---

Flow Title=Flows
Program Version=6.31
Number of Profiles= 1
Profile Names=01pct
River Rch & RM=GETOUTRN,Main            ,10524
     679
River Rch & RM=GETOUTRN,Main            ,8472
     798
River Rch & RM=GETOUTRN,Main            ,5273
     926
River Rch & RM=GETOUTRN,Main            ,0
    1770
Boundary for River Rch & Prof#=GETOUTRN,Main            , 1
Up Type= 0
Dn Type= 1
Dn Known WS=1833.1
DSS Import GetInterval= 0
DSS Import GetPeak= 0
DSS Import FillOption= 0

--- GETOUTRN.g01 (geometry) ---

Geom Title=Geometry
Program Version=6.31

River Reach=GETOUTRN        ,Main
Reach XY= 30
2175234.45500004643649.6910000152175052.54100001643883.916000009
2174821.92200002      643897.5662174447.01800001644232.835999995
2174132.49600005644126.3540000172174124.56900002644294.703999996
     2173914.152644509.2989999952173917.32899998644836.069000021
2173353.01399998644925.5810000152173209.24500002645129.873999998
2173076.03600003645115.0789999962172827.90299998 645480.42400001
     2172384.492645635.6969999972172355.44599998645864.255999997
2172593.47800002646257.0729999992172169.41100003646563.068000019
      2171940.08      646873.7282171900.56000003647105.548999995
2171664.27500001647193.4590000062171792.16100003647402.244000003
2171560.74100003648116.995000005      2171590.53648334.680000022
2171340.99500002648314.019000009     2171072.889648495.132000014
2170770.47100003      648400.4412170442.09699999648434.008000001
2170004.72499998648752.5650000132169756.19100001648586.304000005
     2169618.146648600.6700000172169425.97297117 648783.99286519

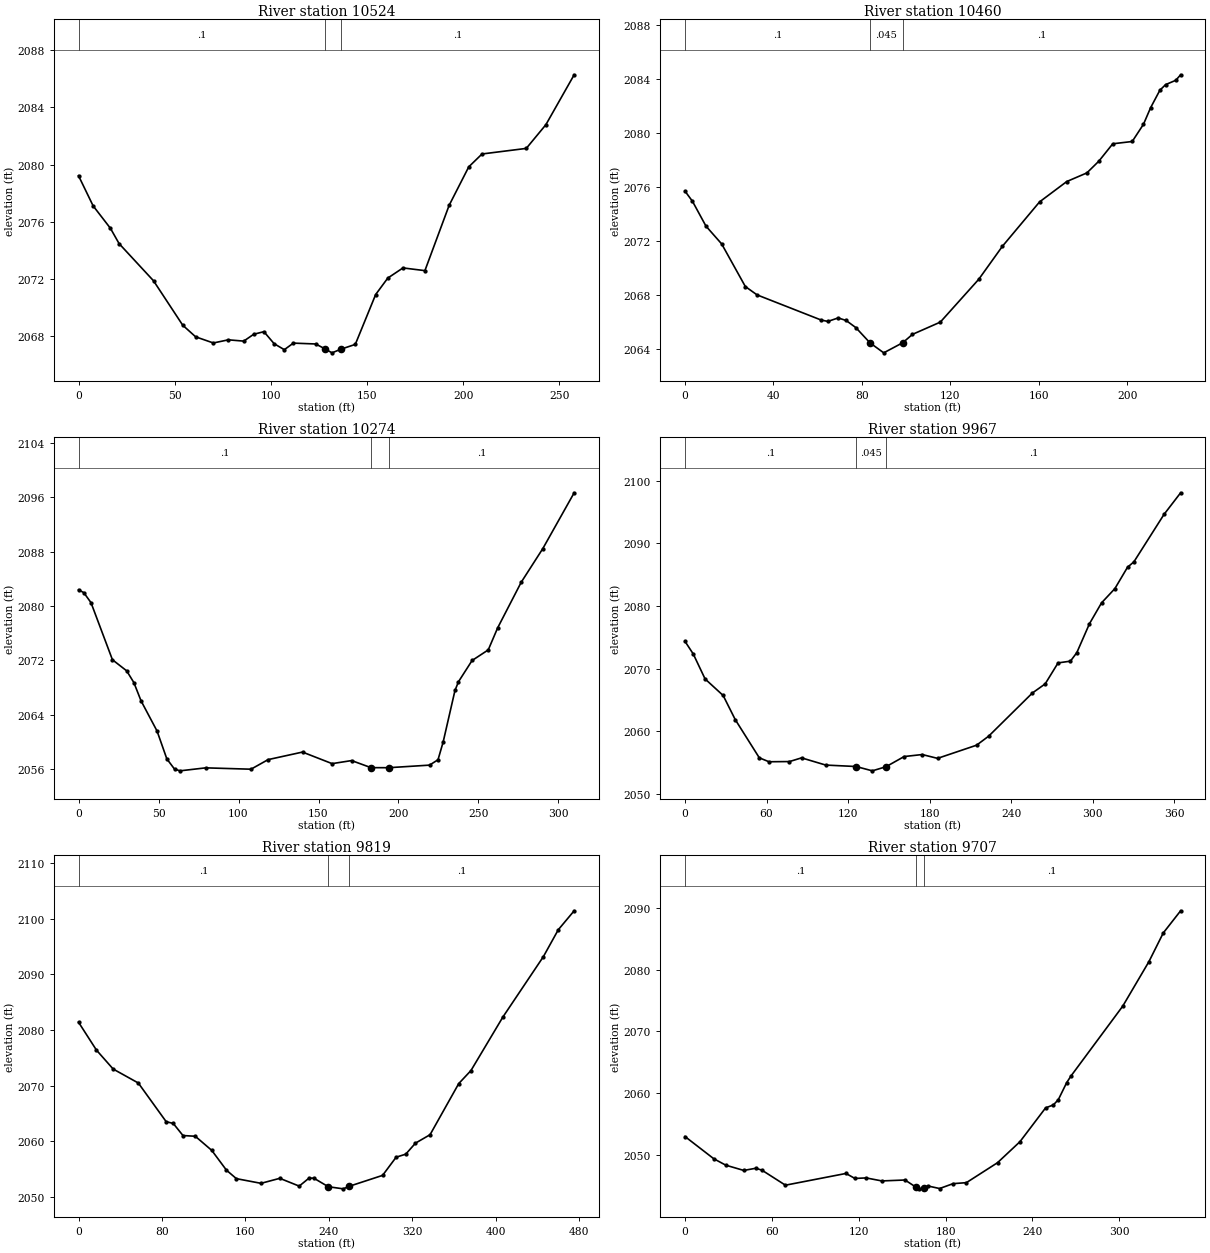
Type RM Length L Ch R = 1 ,10524   ,63.7,63.7,63.7
XS GIS Cut Line= 5
2175113.40010439643596.8021049822175151.31219229643616.145006973
2175241.31365527643693.4133780012175265.98472209 643713.05885714
2175304.81880876643765.142220437
#Sta/Elev= 30
       0 2079.22     7.6 2077.11    16.6 2075.54    21.1 2074.47      39 2071.87
    54.2 2068.76    60.9 2067.95    70.1 2067.52    77.9 2067.74    85.9 2067.65
    91.1 2068.13    96.4 2068.31   101.7 2067.47     107 2067.05   111.7 2067.51
   123.3 2067.45     128 2067.12   131.8 2066.83   136.3 2067.08   143.9 2067.42
   154.5 2070.91   160.8 2072.06   168.7 2072.77   180.1 2072.58   192.7 2077.15
   202.9 2079.84   209.8 2080.74   232.8 2081.13     243 2082.79   257.7 2086.28
#Mann= 3 ,-1,0
       0      .1       0     128    .045       0   136.3      .1       0
Bank Sta=128,136.3
XS Rating Curve= 0 ,0
Exp/Cntr(USF)=0,0
Exp/Cntr=0.3,0.1

Type RM Length L Ch R = 1 ,10460   ,183.7,186,186.7
XS GIS Cut Line= 5
2175099.68345683643650.9243184692175140.80190154643687.017175491
2175198.82459573643733.6180794942175250.45108742643755.091045063
2175281.51835676643778.848368673
#Sta/Elev= 30
       0 2075.71     3.4 2074.95     9.5 2073.11    16.6 2071.79    27.3 2068.63
    32.6 2068.01    61.5 2066.15    64.6 2066.04    69.3  2066.3    72.9 2066.11
    77.3 2065.58    83.7 2064.45    89.9 2063.71    98.5 2064.46   102.9 2065.08
   115.5 2065.99   132.9 2069.17   143.6 2071.62   160.4 2074.91   172.7 2076.42
   181.8 2077.06   187.2 2077.93   193.5 2079.22   202.3 2079.39   207.4 2080.67
   210.6 2081.89   214.8 2083.19   217.4 2083.61     222 2083.93   224.2 2084.34
#Mann= 3 ,-1,0
       0      .1       0    83.7    .045       0    98.5      .1       0
Bank Sta=83.7,98.5
XS Rating Curve= 0 ,0
Exp/Cntr(USF)=0,0
Exp/Cntr=0.3,0.1

Type RM Length L Ch R = 1 ,10274   ,303.3,307,305.8
XS GIS Cut Line= 4
 2174964.4494609643690.2152767462174982.72432521643726.765005376
2175119.32893597643883.015095267 2175155.8786646643932.357228917
#Sta/Elev= 30
       0 2082.39     3.3 2081.97     7.8  2080.5    21.2  2072.1    30.1 2070.47
    34.6 2068.74    39.1 2066.05    49.1 2061.61    55.2 2057.52      60 2056.02
    63.4 2055.76    79.5  2056.2   107.8    2056   118.5 2057.41     140 2058.52
   158.5 2056.82   170.7 2057.27   182.8 2056.23   193.8 2056.22   219.4  2056.6
   224.7 2057.39   227.9 2059.99   235.3 2067.58   237.5 2068.87     246 2071.99
   256.1 2073.55     262  2076.8   276.7  2083.5   290.2 2088.45   309.8 2096.66
#Mann= 3 ,-1,0
       0      .1       0   182.8    .045       0   193.8      .1       0
Bank Sta=182.8,193.8
XS Rating Curve= 0 ,0
Exp/Cntr(USF)=0,0
Exp/Cntr=0.3,0.1

Type RM Length L Ch R = 1 ,9967    ,147.6,148.4,146.6
XS GIS Cut Line= 3
2174769.37090283643771.8550279622174869.66743167 643980.08972594
2174938.44219431644094.714330332
#Sta/Elev= 30
       0 2074.37     6.1 2072.35    14.8 2068.37    28.1 2065.73      37 2061.88
    54.7 2055.79    61.8 2055.16    76.9 2055.19    85.8 2055.78   103.6 2054.63
   125.9  2054.4   137.9 2053.71     148 2054.37   161.3 2055.99   174.6 2056.31
   185.9  2055.7   214.6  2057.8   223.5 2059.24   255.7 2066.13   265.1 2067.58
   274.6 2070.93   283.7 2071.21   288.4 2072.57   297.7 2077.18   306.6 2080.51
   316.4 2082.78   325.7 2086.19   330.4 2087.05   352.6 2094.63   364.8 2098.07
#Mann= 3 ,-1,0
       0      .1       0   125.9    .045       0     148      .1       0
Bank Sta=125.9,148
XS Rating Curve= 0 ,0
Exp/Cntr(USF)=0,0
Exp/Cntr=0.3,0.1

Type RM Length L Ch R = 1 ,9819    ,111.1,111.7,111.4
XS GIS Cut Line= 4
2174631.70452837643764.0087341532174636.00295103643843.959395716
2174800.20269682644122.497184389 2174841.4675544644180.955732628
#Sta/Elev= 30
       0 2081.38    17.2 2076.36    33.2 2072.96    57.3 2070.45      84  2063.5
    90.8 2063.18   100.1 2061.01   111.9 2060.88   127.7 2058.34   141.8 2054.78
   151.3 2053.26   174.9 2052.42   192.9 2053.32   211.5 2051.92   220.8 2053.34
   225.4 2053.36   239.4 2051.81   253.7 2051.43   259.3 2051.88   291.4 2053.85
   304.4 2057.12   313.6 2057.66   322.9 2059.64   336.9 2061.16   364.4 2070.35
   376.1 2072.69   406.7 2082.31   445.5 2093.16   459.8    2098     475  2101.4
#Mann= 3 ,-1,0
       0      .1       0   239.4    .045       0   259.3      .1       0
Bank Sta=239.4,259.3
XS Rating Curve= 0 ,0
Exp/Cntr(USF)=0,0
Exp/Cntr=0.3,0.1

Type RM Length L Ch R = 1 ,9707    ,82.9,82.9,82.6
XS GIS Cut Line= 4
2174600.93322577643897.9514847112174582.87983265643965.006944894
 2174678.3049106644130.0665391922174722.14886534644199.701055537
#Sta/Elev= 30
       0 2052.98    19.9 2049.38    28.2 2048.34    40.6 2047.49    48.9 2047.84
    53.1 2047.54    69.4  2045.1   111.2    2047   117.4 2046.19   125.1 2046.28
     136 2045.79     152 2045.94   159.9 2044.73     162 2044.51   164.9 2044.69
   167.9 2044.97   175.9 2044.56   185.2 2045.35   194.4 2045.51   215.9 2048.74
   231.4 2052.14   249.1 2057.61   254.5  2058.1   257.9 2058.94   263.7 2061.71
   266.6 2062.76   302.4 2074.08   320.5 2081.29   330.4 2085.93   342.4 2089.52
#Mann= 3 ,-1,0
       0      .1       0   159.9    .045       0   164.9      .1       0
Bank Sta=159.9,164.9
XS Rating Curve= 0 ,0
Exp/Cntr(USF)=0,0
Exp/Cntr=0.3,0.1

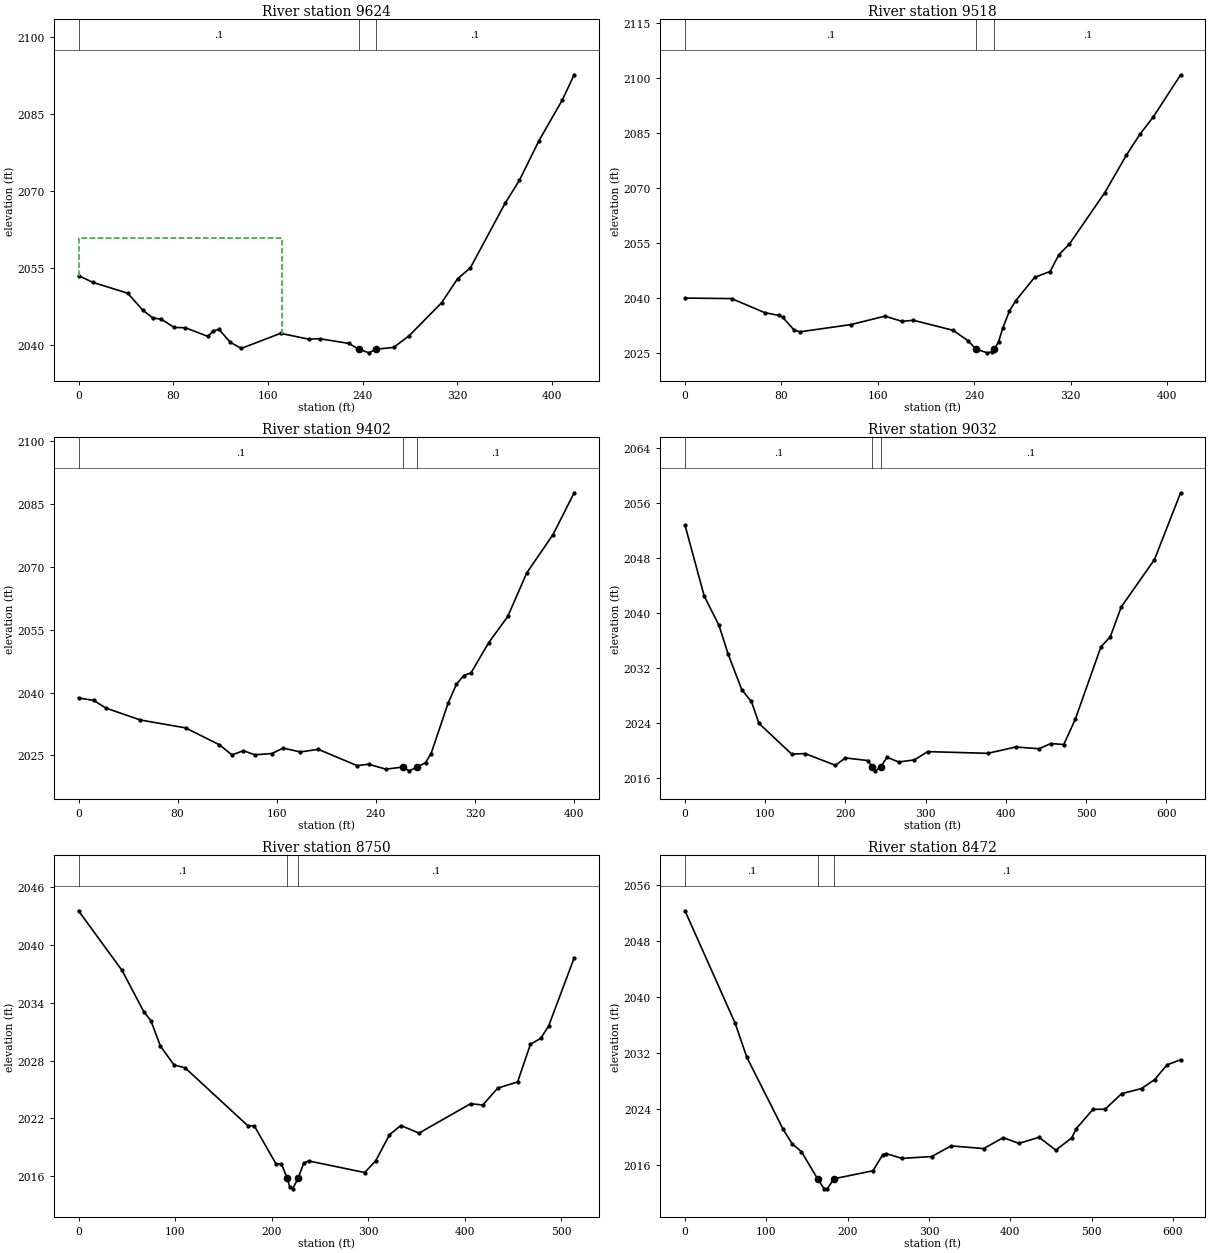
Type RM Length L Ch R = 1 ,9624    ,105.2,106.7,106.6
XS GIS Cut Line= 6
2174497.77097934643885.9158892932174474.76022499643951.780197507
2174512.38563092644011.4299557912174591.47668652644137.803707675
2174623.28504583644199.7010555372174662.83057364644244.404695659
#Sta/Elev= 30
       0 2053.46    11.9 2052.15    41.5 2050.03    54.3 2046.73    62.8 2045.21
    69.8 2044.97    80.9 2043.35    90.3  2043.3   109.3 2041.61     114 2042.72
   118.7 2042.96   128.2 2040.46   137.6 2039.28   170.7 2042.21   194.3 2041.08
   203.7 2041.16   228.5 2040.24   236.7 2039.11   245.5 2038.41   250.9  2039.1
   266.2 2039.47   279.2 2041.72   306.7 2048.16   320.2 2052.84     331 2054.96
   360.3 2067.52   372.4    2072     389 2079.75   408.6 2087.63   418.7 2092.57
#Mann= 3 ,-1,0
       0      .1       0   236.7    .045       0   250.9      .1       0
#XS Ineff= 2 , 0
          171.83 2060.87
Permanent Ineff=
       F       F
Bank Sta=236.7,250.9
XS Rating Curve= 0 ,0
Exp/Cntr(USF)=0,0
Exp/Cntr=0.3,0.1

Type RM Length L Ch R = 1 ,9518    ,115.7,116,115.7
XS GIS Cut Line= 3
2174373.79916849643964.3152303282174531.98112255644218.781852078
2174605.91399238644302.171251773
#Sta/Elev= 30
       0  2039.9    38.7 2039.76    66.2 2035.91    77.9 2035.17    81.1 2034.65
    90.5 2031.17    95.3 2030.69   137.6 2032.66   165.9 2034.97     180 2033.54
   189.4 2033.84   222.4  2031.1   234.7 2028.27   241.2 2026.03   250.6 2024.95
     255 2025.25   256.7 2025.99   260.1 2028.01   263.7 2031.82   269.1 2036.36
   274.2 2039.13   289.9 2045.54   302.8 2047.15     310 2051.67   318.9 2054.68
   348.2 2068.69   366.2 2078.97   377.7 2084.79   388.4 2089.34   411.1 2100.86
#Mann= 3 ,-1,0
       0      .1       0   241.2    .045       0   256.7      .1       0
Bank Sta=241.2,256.7
XS Rating Curve= 0 ,0
Exp/Cntr(USF)=0,0
Exp/Cntr=0.3,0.1

Type RM Length L Ch R = 1 ,9402    ,368.7,370,365.1
XS GIS Cut Line= 4
2174356.16633237644001.4168879122174329.42056478 644089.29583858
2174445.00048902644293.7099194822174490.85037633644351.022278613
#Sta/Elev= 30
       0  2038.7    12.3 2038.11    22.2 2036.27    49.9 2033.44    86.4 2031.55
   113.7 2027.52   123.9  2025.1   133.1  2026.1   142.3 2025.12   156.1 2025.43
   165.2 2026.72     179 2025.81   193.6 2026.42     225 2022.52   234.2 2022.88
     248 2021.69   261.7 2022.19     267 2021.29   272.9 2022.11   280.1 2023.25
   284.6 2025.42   298.5 2037.58   305.1 2041.99     311 2044.06   316.9 2044.72
   331.1 2051.91   346.5 2058.17   361.9 2068.62     383 2077.72   400.1 2087.72
#Mann= 3 ,-1,0
       0      .1       0   261.7    .045       0   272.9      .1       0
Bank Sta=261.7,272.9
XS Rating Curve= 0 ,0
Exp/Cntr(USF)=0,0
Exp/Cntr=0.3,0.1

Type RM Length L Ch R = 1 ,9032    ,277.5,281.5,279.4
XS GIS Cut Line= 4
2173957.70151106643977.2263197042174051.04920789644011.799540755
2174280.38490753644343.7024628392174380.64724858644400.172057221
#Sta/Elev= 30
       0 2052.81      24 2042.47    42.4 2038.21    53.8 2034.03    70.9 2028.82
    82.8 2027.12    92.2 2023.94     133 2019.46   149.8 2019.53   187.6 2017.83
     200  2018.9   227.9 2018.52   233.6 2017.56   237.4 2017.02   243.82017.545
   251.9    2019   266.5 2018.31     286 2018.61   302.6 2019.82   377.4 2019.57
   412.4 2020.49   441.6 2020.24   456.1    2021   472.3 2020.85   486.6 2024.52
   518.6 2035.08   530.3 2036.56     544  2040.9   585.4  2047.8     618 2057.52
#Mann= 3 ,-1,0
       0      .1       0   233.6    .045       0   243.8      .1       0
Bank Sta=233.6,243.8
XS Rating Curve= 0 ,0
Exp/Cntr(USF)=0,0
Exp/Cntr=0.3,0.1

Type RM Length L Ch R = 1 ,8750    ,285,277.8,261.5
XS GIS Cut Line= 5
2173908.30731239644189.349870031 2174027.1772725644295.483762986
2174137.55652117 644454.684602422174199.11417908644473.788703152
2174294.63468274644467.420669574
#Sta/Elev= 30
       0 2043.51    45.1 2037.33    67.8 2033.02    74.9 2032.14    84.8  2029.5
    98.9 2027.54   110.3 2027.25   175.1 2021.27   182.2  2021.2   204.4 2017.32
   210.2 2017.27   215.9 2015.88   218.8 2014.91   221.7 2014.71   227.4  2015.8
   233.2 2017.37   238.3  2017.6   296.4  2016.4   307.9 2017.63     322 2020.31
   333.8 2021.27   352.6 2020.48   406.1 2023.53   418.6 2023.39   434.1 2025.14
   454.7 2025.78     468 2029.68   478.7  2030.3   486.8 2031.56   513.3 2038.63
#Mann= 3 ,-1,0
       0      .1       0   215.9    .045       0   227.4      .1       0
Bank Sta=215.9,227.4
XS Rating Curve= 0 ,0
Exp/Cntr(USF)=0,0
Exp/Cntr=0.3,0.1

Type RM Length L Ch R = 1 ,8472    ,169.1,169.7,170.5
XS GIS Cut Line= 5
2173759.09841976644461.0409989162173872.66168522644535.334723985
2173988.34762854644533.2120461262174133.61020088644528.679818857
2174301.44261276644659.511378743
#Sta/Elev= 30
       0 2052.28    61.6 2036.25      76 2031.38   120.8 2021.06   131.8 2019.01
   143.2 2017.89   163.2 2013.99   171.2 2012.58   175.2 2012.62   183.2 2014.02
   231.2 2015.16   243.2 2017.46   247.2 2017.62   266.8 2016.93   303.3 2017.19
   327.3 2018.71   367.3 2018.33   391.3 2019.89   410.6 2019.07   435.5 2019.94
   455.9  2018.1   475.6 2019.86   481.1 2021.17   501.7 2023.93   516.6 2023.95
   536.9 2026.17   561.4  2026.9   577.5 2028.17   592.7 2030.28   609.5 2031.01
#Mann= 3 ,-1,0
       0      .1       0   163.2    .045       0   183.2      .1       0
Bank Sta=163.2,183.2
XS Rating Curve= 0 ,0
Exp/Cntr(USF)=0,0
Exp/Cntr=0.3,0.1

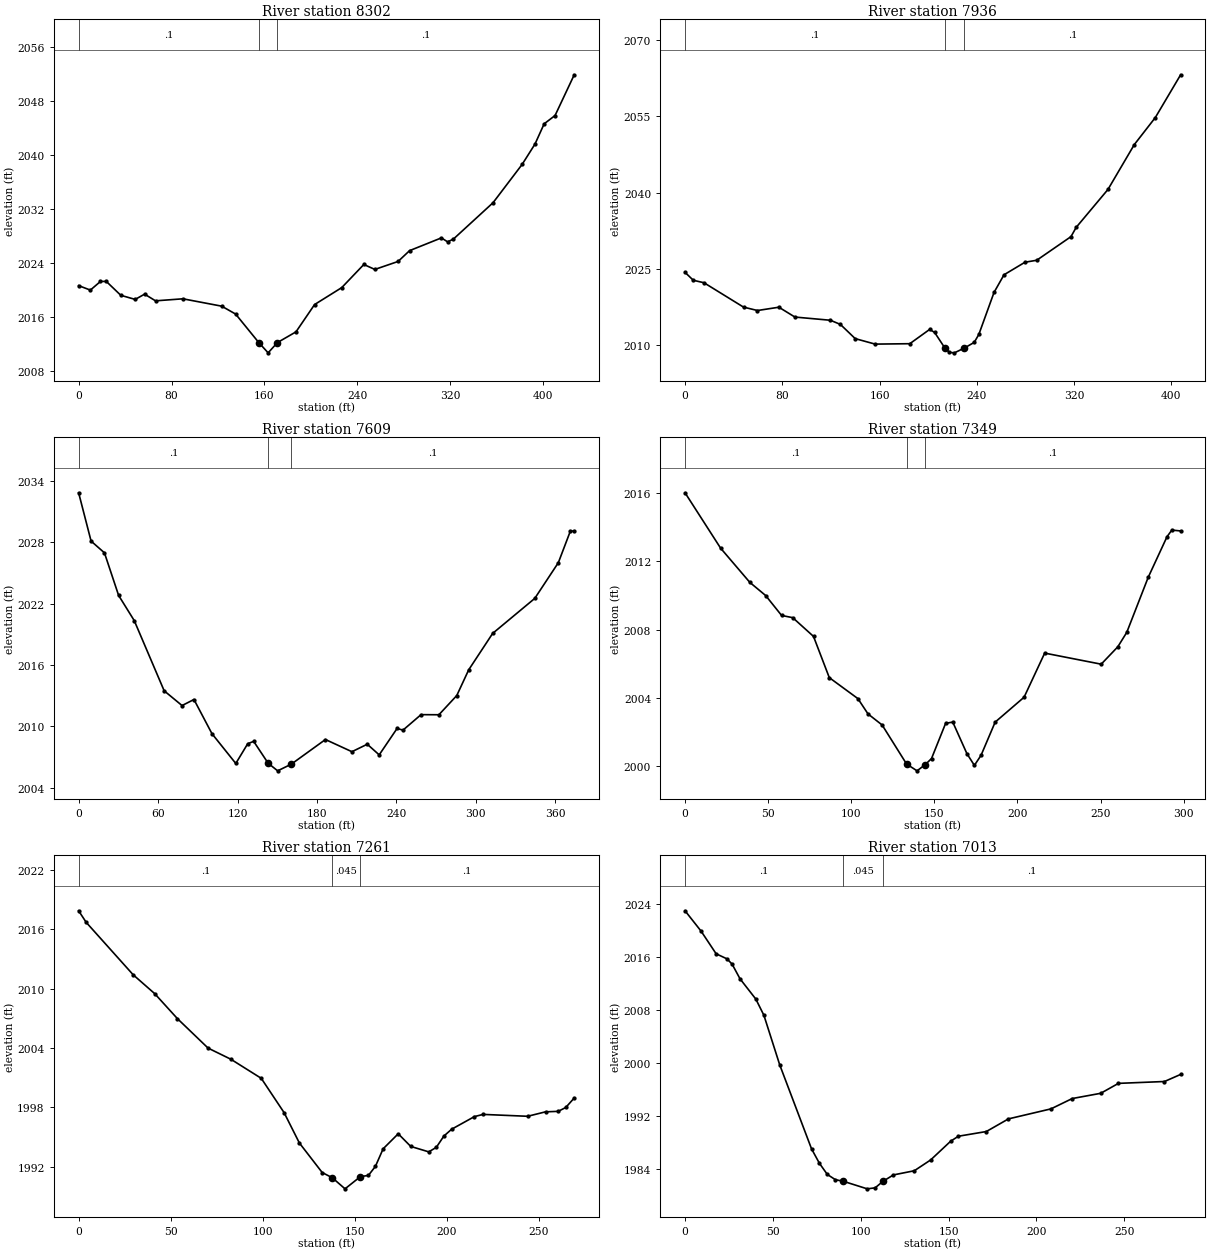
Type RM Length L Ch R = 1 ,8302    ,349.1,366.2,375.7
XS GIS Cut Line= 5
2173723.99852915 644647.388238462173807.85740754 644699.80003745
2173920.54277537 644699.80003745 2173980.8163442644743.039771617
2174062.05463264644858.345729396
#Sta/Elev= 30
       0  2020.6    10.1 2019.94    18.8 2021.22    23.8 2021.23    36.3 2019.17
    48.7 2018.56    56.8 2019.34    66.2 2018.35    89.8 2018.65   123.2 2017.56
   135.2 2016.39   155.2 2012.16   163.2 2010.65   171.2 2012.17   187.2 2013.76
   203.2  2017.8   226.6 2020.31   245.6 2023.73   255.1    2023   275.1 2024.18
     285 2025.78   312.4 2027.67   317.7 2027.09   322.6 2027.47   356.9 2032.88
   381.9 2038.54     393 2041.56   400.9 2044.56   410.3 2045.79   426.8 2051.82
#Mann= 3 ,-1,0
       0      .1       0   155.2    .045       0   171.2      .1       0
Bank Sta=155.2,171.2
XS Rating Curve= 0 ,0
Exp/Cntr(USF)=0,0
Exp/Cntr=0.3,0.1

Type RM Length L Ch R = 1 ,7936    ,329.3,327.1,322.8
XS GIS Cut Line= 4
2173646.69112564644670.9735480052173688.62056483644762.694196239
2173723.99852915644942.2046077812173772.47944322645056.200270585
#Sta/Elev= 30
       0 2024.28     6.8 2022.72    15.6 2022.23    48.1 2017.43    59.6 2016.76
    77.2 2017.41    90.4 2015.47   119.6 2014.84   127.8 2014.02     140 2011.22
   156.4 2010.14   184.9 2010.22   201.2 2013.03   205.3 2012.45   213.5 2009.46
   217.5 2008.51   221.6 2008.42   229.8 2009.37   237.9 2010.48   241.7 2012.05
   254.2 2020.33   262.4  2023.8   279.7 2026.28   289.3 2026.66   317.5 2031.32
   321.8 2033.15   347.9 2040.61   369.6 2049.46   386.9 2054.79   407.7 2063.21
#Mann= 3 ,-1,0
       0      .1       0   213.5    .045       0   229.8      .1       0
Bank Sta=213.5,229.8
XS Rating Curve= 0 ,0
Exp/Cntr(USF)=0,0
Exp/Cntr=0.3,0.1

Type RM Length L Ch R = 1 ,7609    ,256,260.4,256.9
XS GIS Cut Line= 2
2173328.72481716644791.9234277432173501.81634829645123.822237437
#Sta/Elev= 30
       0 2032.83     9.4 2028.11    19.5 2026.96    30.2  2022.8      42 2020.34
    64.6 2013.48    78.1 2012.04    87.1 2012.63   100.7 2009.29   118.7 2006.38
   127.7 2008.31   132.2 2008.54   143.1 2006.41   150.3 2005.66   160.6 2006.31
   186.4 2008.72   206.4 2007.53     218 2008.26     227 2007.22   240.5  2009.8
     245 2009.64   258.6 2011.15   272.1 2011.14   285.6 2013.02   294.6 2015.53
   312.7 2019.09   344.5 2022.51   362.3    2026   371.3 2029.06   374.3 2029.11
#Mann= 3 ,-1,0
       0      .1       0   143.1    .045       0   160.6      .1       0
Bank Sta=143.1,160.6
XS Rating Curve= 0 ,0
Exp/Cntr(USF)=0,0
Exp/Cntr=0.3,0.1

Type RM Length L Ch R = 1 ,7349    ,87.3,87.5,85.1
XS GIS Cut Line= 4
2173187.07167016644972.6033788562173244.72464905645060.393142165
2173277.48202342645152.1137903982173348.02999239645216.862624052
#Sta/Elev= 30
       0 2016.03    21.4 2012.78      39 2010.77    48.5    2010    58.1 2008.83
    64.8  2008.7    77.3  2007.6    86.8 2005.18     104 2003.95   110.1 2003.05
   118.6  2002.4   133.32000.111   139.6 1999.71   144.62000.082   148.3 2000.43
   156.8  2002.5   161.1 2002.57   169.6 2000.72   174.1 2000.03   178.1 2000.62
   186.6 2002.57     204 2004.03   216.4 2006.62   250.4 2005.97   260.4 2006.99
   265.8 2007.84   278.7 2011.07     290 2013.45   292.9 2013.84   298.2 2013.79
#Mann= 3 ,-1,0
       0      .1       0   133.3    .045       0   144.6      .1       0
Bank Sta=133.3,144.6
XS Rating Curve= 0 ,0
Exp/Cntr(USF)=0,0
Exp/Cntr=0.3,0.1

Type RM Length L Ch R = 1 ,7261    ,254,248.4,239.8
XS GIS Cut Line= 2
2173148.07103467644985.1809625022173216.13129691645245.658509351
#Sta/Elev= 30
       0 2017.89     4.1 2016.72    29.6 2011.42    41.3 2009.51    53.7 2006.97
    70.3    2004    82.7 2002.87    99.2 2000.94   111.6 1997.47   119.9  1994.4
   132.3 1991.41   137.8 1990.88   144.7 1989.76     153 1990.99   157.4 1991.12
   161.2 1992.03   165.4 1993.81   173.6 1995.33   180.4 1994.05   190.2  1993.5
   194.3 1993.96   198.4  1995.1   202.6 1995.79     215 1997.07   219.7 1997.29
   243.9  1997.1   253.6 1997.55   260.5  1997.6   264.6 1997.99   269.2 1998.95
#Mann= 3 ,-1,0
       0      .1       0   137.8    .045       0     153      .1       0
Bank Sta=137.8,153
XS Rating Curve= 0 ,0
Exp/Cntr(USF)=0,0
Exp/Cntr=0.3,0.1

Type RM Length L Ch R = 1 ,7013    ,85.7,86.4,86.4
XS GIS Cut Line= 3
2172952.50162848645176.5845861442173108.20004945645258.732219291
2173213.27260348645244.404143742
#Sta/Elev= 30
       0 2023.02     9.1 2019.96    17.7 2016.53    23.9 2015.76    26.8 2014.96
    31.3 2012.75    40.3 2009.69    44.9 2007.24    53.9 1999.76      72 1987.09
    76.5  1984.9      81 1983.22    85.6 1982.43    90.1 1982.19   103.7 1981.05
   108.2  1981.2   112.7 1982.19   118.6 1983.15   130.5 1983.78   139.8 1985.41
   151.2 1988.24   155.6 1988.99   171.5  1989.7   184.1 1991.61   208.3 1993.12
   220.4 1994.68   236.6 1995.47   246.7 1996.97   272.9 1997.25   282.1 1998.32
#Mann= 3 ,-1,0
       0      .1       0    90.1    .045       0   112.7      .1       0
Bank Sta=90.1,112.7
XS Rating Curve= 0 ,0
Exp/Cntr(USF)=0,0
Exp/Cntr=0.3,0.1

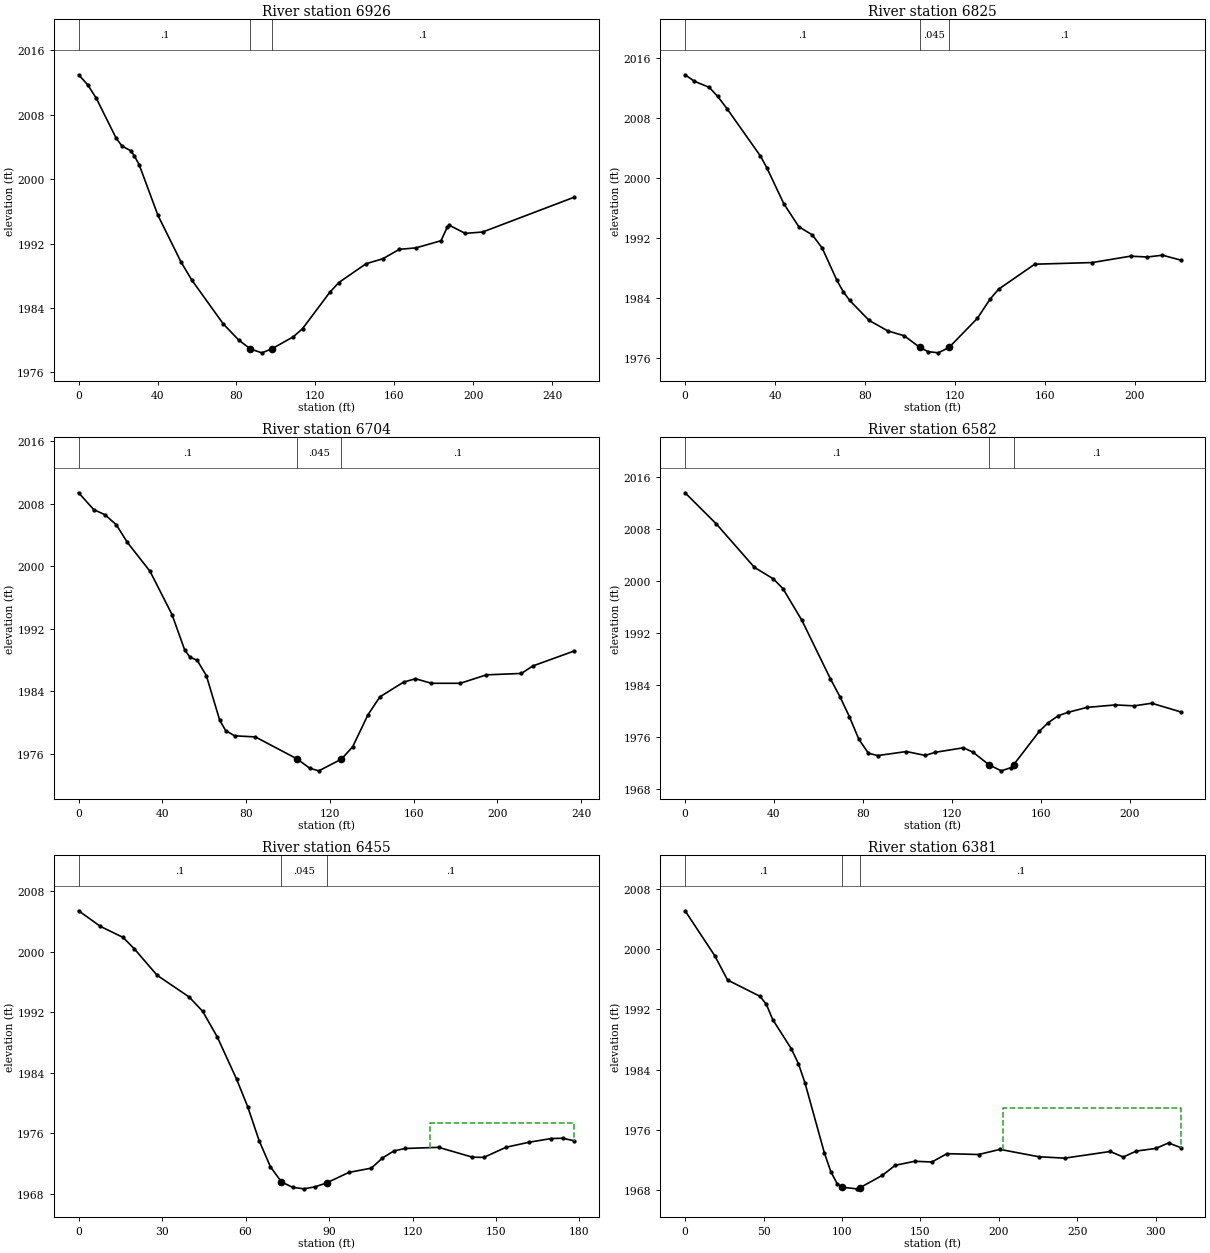
Type RM Length L Ch R = 1 ,6926    ,99.4,101.3,103.2
XS GIS Cut Line= 4
2172919.93948807645256.4169280712172953.37166435 645270.74500362
2173047.93696297645325.1916907062173148.23349181645358.623866987
#Sta/Elev= 30
       0 2012.96     4.6 2011.72       9 2010.02      19  2005.1      22 2004.11
    26.4 2003.53    28.2 2002.91    30.7 2001.79    40.2 1995.51    51.9 1989.72
    57.3  1987.5    73.3 1982.04    81.1 1980.04    87.1 1978.92    92.9 1978.44
    98.11978.957   108.8 1980.43   113.5 1981.44   127.3 1985.95   131.9 1987.17
   145.7  1989.5   154.2 1990.12   162.6 1991.29     171 1991.47   183.7 1992.36
   186.8 1994.01   187.9 1994.28     196 1993.27   204.8 1993.44   251.2 1997.76
#Mann= 3 ,-1,0
       0      .1       0    87.1    .045       0    98.1      .1       0
Bank Sta=87.1,98.1
XS Rating Curve= 0 ,0
Exp/Cntr(USF)=0,0
Exp/Cntr=0.3,0.1

Type RM Length L Ch R = 1 ,6825    ,119.3,121.5,122.3
XS GIS Cut Line= 3
2172856.98112482645309.3580862312172909.51740184645352.342312878
 2173026.0524163645450.728431648
#Sta/Elev= 30
       0 2013.74     4.1 2012.88    10.7 2012.07    14.5 2010.86    18.7  2009.2
    33.4 2002.96    36.3 2001.38    43.9 1996.56    50.6 1993.49    56.6  1992.4
      61 1990.64    67.5 1986.36    70.4 1984.81    73.2 1983.68    81.8 1981.02
    90.2 1979.61    97.5 1978.96   104.4 1977.41     108 1976.86   112.6 1976.69
   117.4 1977.41     130 1981.29   135.6 1983.83   139.4 1985.16   155.5  1988.5
   181.1 1988.72   198.1 1989.57   205.6 1989.46   212.3  1989.7   220.4 1989.05
#Mann= 3 ,-1,0
       0      .1       0   104.4    .045       0   117.4      .1       0
Bank Sta=104.4,117.4
XS Rating Curve= 0 ,0
Exp/Cntr(USF)=0,0
Exp/Cntr=0.3,0.1

Type RM Length L Ch R = 1 ,6704    ,118,121.2,124.4
XS GIS Cut Line= 2
2172778.39214139645375.809636562 2172936.5621795645551.953542634
#Sta/Elev= 30
       0 2009.42     7.2 2007.27    12.6 2006.61      18 2005.33    23.3 2003.06
    34.1 1999.38    44.6 1993.84    50.6 1989.36    53.2 1988.38    56.6    1988
      61 1986.04    67.4 1980.32    70.2 1979.01    74.5 1978.33    84.4 1978.19
   104.4 1975.37   110.4 1974.18   114.7 1973.85   125.5 1975.34   130.9 1976.93
   138.2 1981.02   143.9 1983.31   155.2  1985.2   160.9 1985.63   168.5 1985.05
   182.3 1985.05   194.8 1986.13   211.5 1986.31   216.9 1987.26   236.7 1989.18
#Mann= 3 ,-1,0
       0      .1       0   104.4    .045       0   125.5      .1       0
Bank Sta=104.4,125.5
XS Rating Curve= 0 ,0
Exp/Cntr(USF)=0,0
Exp/Cntr=0.3,0.1

Type RM Length L Ch R = 1 ,6582    ,125.8,127.3,128.7
XS GIS Cut Line= 3
2172702.90189593645391.9861177322172776.59475459645587.901278567
2172782.26072179645600.304588009
#Sta/Elev= 30
       0 2013.62    14.1 2008.81    31.2 2002.14    39.7 2000.38      44 1998.89
    52.6 1993.97    65.4 1984.99    69.7 1982.24    73.9  1979.2    78.2 1975.69
    82.5 1973.55    86.7 1973.19    99.6 1973.81   108.1 1973.21   112.4 1973.68
   125.2 1974.39   129.5 1973.72   136.9 1971.74   142.3 1970.84   146.6 1971.33
   147.9  1971.8   159.4 1976.92   163.4 1978.25   167.9 1979.31   172.2 1979.83
   180.8  1980.6   193.6 1980.98   202.1 1980.84     210 1981.24     223 1979.91
#Mann= 3 ,-1,0
       0      .1       0   136.9    .045       0   147.9      .1       0
Bank Sta=136.9,147.9
XS Rating Curve= 0 ,0
Exp/Cntr(USF)=0,0
Exp/Cntr=0.3,0.1

Type RM Length L Ch R = 1 ,6455    ,75.6,74.5,73.6
XS GIS Cut Line= 4
2172612.81690035 645445.561372082172624.42264154645501.268929815
 2172633.7072345645574.7719573812172641.44439529 645621.19492216
#Sta/Elev= 30
       0 2005.41     7.8 2003.35      16 2001.88      20 2000.38    28.2 1996.88
    39.7 1994.01    44.6  1992.1    49.9 1988.66    56.8 1983.11    60.8 1979.45
    64.9 1974.97    68.9 1971.56    72.9 1969.53      77 1968.81      81 1968.62
      85 1968.89    89.1  1969.4    97.1 1970.79   105.2 1971.36   109.2  1972.7
   113.3 1973.63   117.3 1973.96   129.4 1974.11   141.5 1972.81   145.6 1972.78
   153.7 1974.13   161.8 1974.78   169.9 1975.28     174 1975.31   178.1 1974.98
#Mann= 3 ,-1,0
       0      .1       0    72.9    .045       0    89.1      .1       0
#XS Ineff= 2 , 0
                          126.42         1977.33
Permanent Ineff=
       F       F
Bank Sta=72.9,89.1
XS Rating Curve= 0 ,0
Exp/Cntr(USF)=0,0
Exp/Cntr=0.3,0.1

Type RM Length L Ch R = 1 ,6381    ,194,187.8,177
XS GIS Cut Line= 3
2172532.75163296645446.8413476832172578.20722784  645636.1009476
2172695.61421554645666.729579562
#Sta/Elev= 30
       0 2005.07    18.9 1999.12    27.1 1995.89    47.7 1993.74    51.8 1992.68
    55.9 1990.64    67.8 1986.76    72.3 1984.79    76.5 1982.22    88.8 1972.99
    92.9 1970.51      97 1968.89    99.91968.437   109.4 1968.22   111.61968.381
   125.8 1970.01     134 1971.34   146.4 1971.87   157.4 1971.78     167 1972.88
   187.2 1972.77   200.8 1973.45   225.6 1972.47   242.1 1972.29   271.1 1973.17
   279.4 1972.43   287.6 1973.22     300 1973.57   308.3  1974.3     316 1973.69
#Mann= 3 ,-1,0
       0      .1       0    99.9    .045       0   111.6      .1       0
#XS Ineff= 2 , 0
                           202.7          1978.9
Permanent Ineff=
       F       F
Bank Sta=99.9,111.6
XS Rating Curve= 0 ,0
Exp/Cntr(USF)=0,0
Exp/Cntr=0.3,0.1

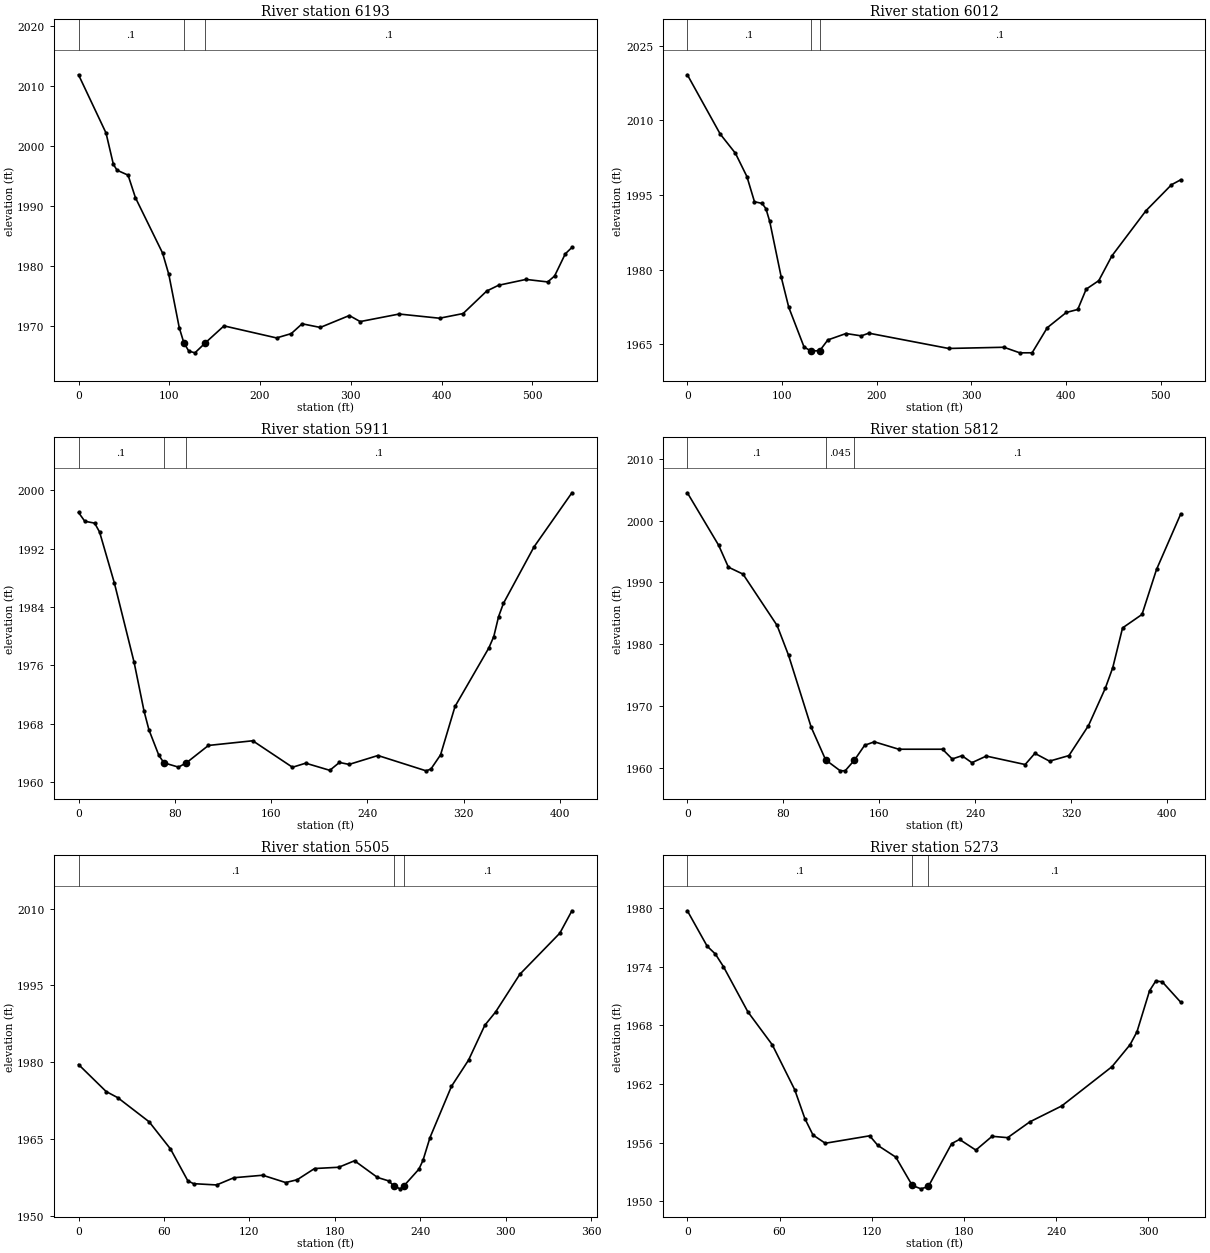
Type RM Length L Ch R = 1 ,6193    ,186.3,180.9,171.2
XS GIS Cut Line= 5
2172274.20556375645593.4249043872172355.92866133645606.160971542
2172432.34506425 645657.105240162172610.65000442 645658.16657909
2172786.83226673645731.398965229
#Sta/Elev= 30
       0 2011.93    30.3 2002.21    38.4 1996.97    42.5 1995.99    54.6 1995.17
    62.7 1991.41    92.6 1982.17    99.5 1978.59     111  1969.7     116 1967.21
   121.5 1965.79   128.3  1965.5   139.9 1967.19   160.3    1970   218.2 1967.99
   234.4 1968.71   246.4 1970.35   266.4 1969.74   298.4 1971.73   310.4 1970.72
   353.3 1971.98   397.8 1971.28   423.8 1972.06   449.8 1975.82   462.8 1976.78
   493.1 1977.76     517 1977.34   524.6 1978.33   536.4 1982.03   543.7  1983.1
#Mann= 3 ,-1,0
       0      .1       0     116    .045       0   139.9      .1       0
Bank Sta=116,139.9
XS Rating Curve= 0 ,0
Exp/Cntr(USF)=0,0
Exp/Cntr=0.3,0.1

Type RM Length L Ch R = 1 ,6012    ,102.5,101.1,99.4
XS GIS Cut Line= 5
2172213.70924477645791.8952842142172298.61635913 645801.44733458
2172407.93426887645788.7112674252172623.38607157645804.631351369
2172722.09059202645852.391603199
#Sta/Elev= 30
       0 2019.15    34.7 2007.25    50.8 2003.38    62.9 1998.71    70.9 1993.65
      79 1993.31      83 1992.25      87 1989.71    99.1 1978.57   107.1 1972.46
   123.3 1964.46   130.4 1963.69   139.81963.722   148.4 1965.89   167.6 1967.18
   183.7 1966.71   191.7 1967.25     276 1964.18   334.4 1964.42   351.2  1963.3
   364.2 1963.31   380.2 1968.35   400.3 1971.41   412.4 1972.01   421.3 1976.09
   434.6  1977.8   448.5 1982.78   484.4 1991.83   511.4 1997.06   521.2 1998.06
#Mann= 3 ,-1,0
       0      .1       0   130.4    .045       0   139.8      .1       0
Bank Sta=130.4,139.8
XS Rating Curve= 0 ,0
Exp/Cntr(USF)=0,0
Exp/Cntr=0.3,0.1

Type RM Length L Ch R = 1 ,5911    ,97.7,98.6,98.6
XS GIS Cut Line= 6
2172287.13556312645911.7649457552172338.20082438 645900.15920456
2172417.89358058645880.8163025692172607.45402009645877.721438251
 2172641.4975276645873.0791417732172689.46792454645891.648327684
#Sta/Elev= 30
       0 1996.96     5.2 1995.76    13.4  1995.5    17.5 1994.28    29.8 1987.28
    46.2 1976.41    54.4 1969.76    58.5 1967.17    66.7 1963.69    70.9 1962.66
      83 1962.07    89.6 1962.66   107.9 1965.04   144.7 1965.68   177.7 1962.05
   188.7 1962.61   208.7 1961.63   216.7 1962.71   224.7 1962.44   248.7 1963.66
   288.7 1961.56   292.7 1961.81   300.7 1963.75   312.7 1970.38   340.8  1978.4
   344.9 1979.96   348.9  1982.7   352.9  1984.5   378.3 1992.24   409.8 1999.66
#Mann= 3 ,-1,0
       0      .1       0    70.9    .045       0    89.6      .1       0
Bank Sta=70.9,89.6
XS Rating Curve= 0 ,0
Exp/Cntr(USF)=0,0
Exp/Cntr=0.3,0.1

Type RM Length L Ch R = 1 ,5812    ,307.6,307.4,307.8
XS GIS Cut Line= 2
2172274.42005253646004.6428009492172680.05921548645936.582538708
#Sta/Elev= 30
       0 2004.49    26.1 1995.99    34.2 1992.45    46.4 1991.32    74.8 1983.01
    84.4 1978.16   103.2 1966.55   115.3 1961.24   127.5 1959.47   131.6 1959.49
   139.3 1961.21   147.8 1963.61   155.9 1964.17   176.2 1962.97   212.7 1962.97
   220.8 1961.39   228.9 1961.92   237.2 1960.79   249.2 1961.86   281.6 1960.49
   289.7  1962.3   301.9 1961.04   318.1 1961.94   334.4  1966.8   348.4 1972.84
   354.6 1976.16   362.8 1982.61     379 1984.79   391.1 1992.07   411.3 2001.07
#Mann= 3 ,-1,0
       0      .1       0   115.3    .045       0   139.3      .1       0
Bank Sta=115.3,139.3
XS Rating Curve= 0 ,0
Exp/Cntr(USF)=0,0
Exp/Cntr=0.3,0.1

Type RM Length L Ch R = 1 ,5505    ,222.6,231.2,237.5
XS GIS Cut Line= 5
2172365.35240018646166.885415966 2172428.7197471646182.204994343
2172545.00927388646199.6136061352172633.44502178 646197.52457272
2172708.65022472646192.650161418
#Sta/Elev= 30
       0 1979.53    19.4 1974.25    27.6 1973.04    49.6 1968.33    64.6 1963.02
    76.8 1956.78    80.8 1956.23      97 1955.98   109.1 1957.39   129.4 1957.88
   145.5 1956.45   153.6    1957   165.8 1959.19   182.8 1959.44   193.9 1960.71
     210 1957.45     218 1956.76   221.31955.811     226 1955.22   228.6 1955.81
   239.1 1959.06     242  1960.8   246.9 1965.25     262 1975.27     274  1980.4
   285.4  1987.2     293 1989.81     310 1997.17   338.1 2005.21   346.6 2009.59
#Mann= 3 ,-1,0
       0      .1       0   221.3    .045       0   228.6      .1       0
Bank Sta=221.3,228.6
XS Rating Curve= 0 ,0
Exp/Cntr(USF)=0,0
Exp/Cntr=0.3,0.1

Type RM Length L Ch R = 1 ,5273    ,85.5,86.3,86.9
XS GIS Cut Line= 4
 2172354.4493016646232.2822937512172420.15795381646289.388965725
2172517.57322114 646400.618342732172535.49886423646485.055336971
#Sta/Elev= 30
       0 1979.71    12.9 1976.09    18.2  1975.3    23.5    1974    39.4 1969.38
    55.3 1966.01    69.9 1961.42    76.5 1958.47    81.8 1956.79    89.8 1955.95
   118.7 1956.71     124 1955.73   135.7 1954.53   146.4 1951.64   152.1 1951.29
   156.91951.533   172.1 1955.92   177.2 1956.34   187.8 1955.25   198.4 1956.66
   208.5 1956.52     223 1958.14   243.7 1959.76   276.4 1963.77   288.2 1966.02
   292.7 1967.34   300.9 1971.54   304.9 1972.52   309.1 1972.46   321.2 1970.36
#Mann= 3 ,-1,0
       0      .1       0   146.4    .045       0   156.9      .1       0
Bank Sta=146.4,156.9
XS Rating Curve= 0 ,0
Exp/Cntr(USF)=0,0
Exp/Cntr=0.3,0.1