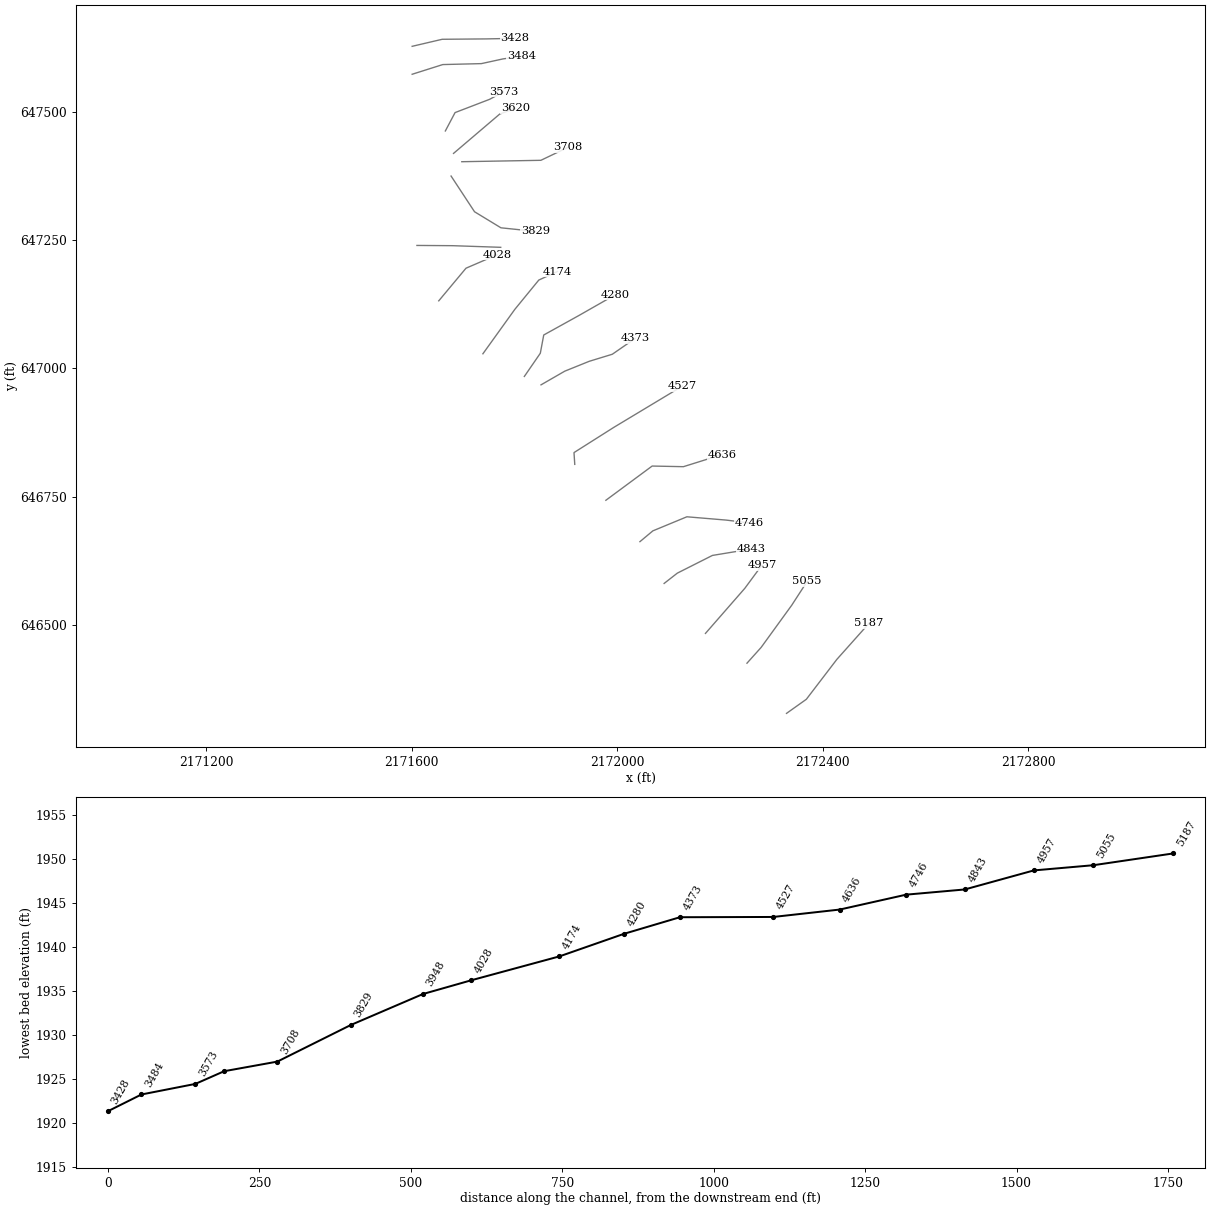
HEC-RAS study GETOUTRN.prj: GETOUTRN

--- GETOUTRN.g01 (geometry) --- (continued)

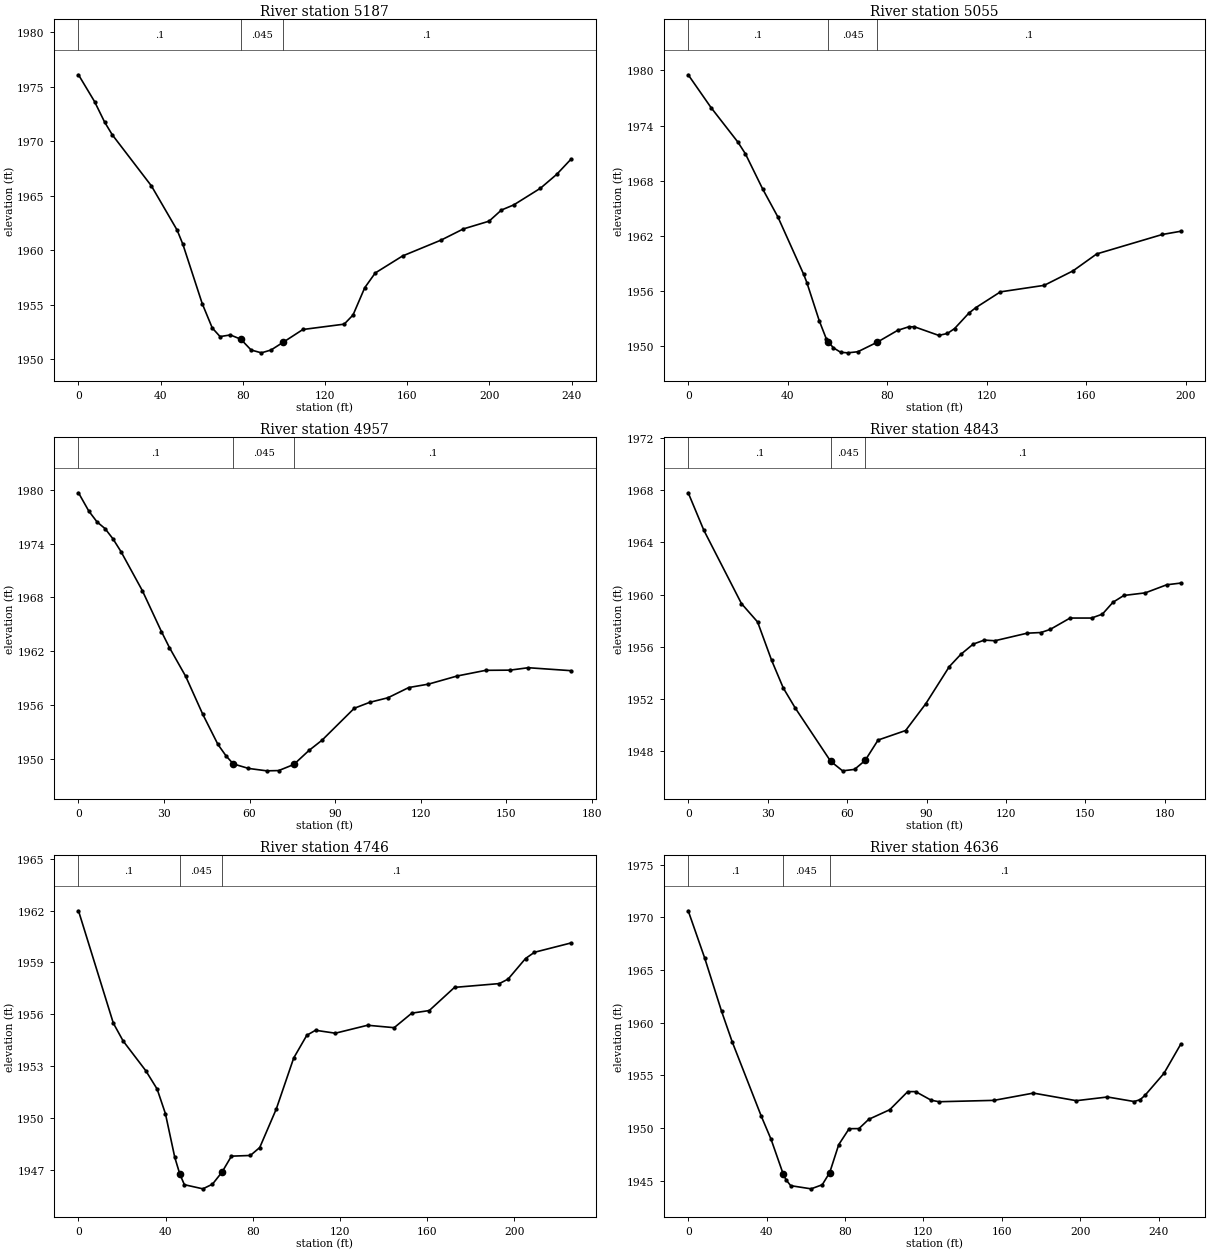
Type RM Length L Ch R = 1 ,5187    ,132.1,132.3,132.8
XS GIS Cut Line= 4
2172329.79116204646328.6342409662172368.37143115646356.046537438
2172427.76474017646433.7147107762172490.71149504646504.275992436
#Sta/Elev= 30
       0 1976.08     7.8 1973.63    12.7 1971.75    16.4 1970.59    35.5 1965.89
      48 1961.84    50.8 1960.54    60.2 1955.11    65.1 1952.87    68.9 1952.08
    73.9 1952.23      79 1951.84      84 1950.85      89 1950.59    93.7 1950.85
    99.7 1951.57   109.2 1952.73   129.3 1953.22   133.6 1954.06   139.3 1956.56
   144.4 1957.91   157.7 1959.47   176.5 1960.93   187.3 1961.95   199.8 1962.66
   205.8 1963.68   211.8 1964.15   224.8 1965.68   232.7 1966.95   239.7 1968.35
#Mann= 3 ,-1,0
       0      .1       0      79    .045       0    99.7      .1       0
Bank Sta=79,99.7
XS Rating Curve= 0 ,0
Exp/Cntr(USF)=0,0
Exp/Cntr=0.3,0.1

Type RM Length L Ch R = 1 ,5055    ,99.2,98.2,97.1
XS GIS Cut Line= 4
2172252.81181879646426.3240414792172280.38705987 646457.03283268
 2172339.9245122646539.1318458912172370.00659337646585.508387705
#Sta/Elev= 30
       0 1979.53     9.2 1975.95      20 1972.19      23 1970.92    29.9 1967.11
    36.1 1964.02    46.4 1957.81    47.7  1956.9    52.7 1952.73    55.5 1950.78
    56.3 1950.44    58.4 1949.79    61.3 1949.31    64.1 1949.25    68.2 1949.37
      76 1950.41    84.2  1951.7    88.6 1952.08    90.9 1952.09   100.7 1951.15
   104.2 1951.36   107.1  1951.9   112.8 1953.57   115.6 1954.17   125.5 1955.89
   143.1  1956.6   154.7 1958.18   164.2 1960.02   190.6 1962.14     198 1962.49
#Mann= 3 ,-1,0
       0      .1       0    56.3    .045       0      76      .1       0
Bank Sta=56.3,76
XS Rating Curve= 0 ,0
Exp/Cntr(USF)=0,0
Exp/Cntr=0.3,0.1

Type RM Length L Ch R = 1 ,4957    ,117.5,114,109.4
XS GIS Cut Line= 3
2172171.99235579646484.2979080692172248.59024768646572.037311501
2172282.01478232 646617.29970216
#Sta/Elev= 30
       0 1979.67     3.6 1977.64     6.5 1976.42     9.3 1975.68    12.1 1974.53
    14.9 1973.11    22.4 1968.75    29.1 1964.18    31.9  1962.4    37.6 1959.19
    43.6 1954.95    48.9  1951.6    51.8  1950.3    54.3 1949.43    59.6 1948.93
      66 1948.66    70.2 1948.69    75.5 1949.37    80.8 1950.93    85.4 1952.08
    96.7 1955.64   102.1  1956.3   108.5 1956.81   115.8 1957.95   122.7 1958.33
   132.8 1959.24   142.8 1959.87   151.3 1959.89   157.7 1960.16   172.7 1959.83
#Mann= 3 ,-1,0
       0      .1       0    54.3    .045       0    75.5      .1       0
Bank Sta=54.3,75.5
XS Rating Curve= 0 ,0
Exp/Cntr(USF)=0,0
Exp/Cntr=0.3,0.1

Type RM Length L Ch R = 1 ,4843    ,97.2,96.7,95.4
XS GIS Cut Line= 4
2172091.53044727646581.5745561892172117.22555827646601.629276973
2172185.53695094646636.0983283222172261.36886391646648.632528812
#Sta/Elev= 30
       0 1967.81     5.9 1964.94    20.1 1959.32    26.2 1957.91    31.5 1954.97
    35.9 1952.85    40.4 1951.32    53.8 1947.23    58.3  1946.5    62.8 1946.61
    66.81947.294    71.7 1948.86    82.1 1949.59    89.7 1951.64    98.6 1954.49
   102.9 1955.42   107.6 1956.21   111.8 1956.52   115.8 1956.47     128 1957.05
   133.2  1957.1   136.7 1957.34   144.2 1958.21   152.3 1958.21   156.4 1958.51
   160.4 1959.42   164.5 1959.94   172.6 1960.14   180.7 1960.76     186 1960.89
#Mann= 3 ,-1,0
       0      .1       0    53.8    .045       0    66.8      .1       0
Bank Sta=53.8,66.8
XS Rating Curve= 0 ,0
Exp/Cntr(USF)=0,0
Exp/Cntr=0.3,0.1

Type RM Length L Ch R = 1 ,4746    ,106.2,109.7,111.5
XS GIS Cut Line= 5
2172044.45108498646662.8967275072172069.57902341646683.912821469
2172135.82540655646711.3251179412172212.12296507646704.928915431
2172256.89638264646699.446456137
#Sta/Elev= 30
       0 1961.99      16 1955.49    20.5 1954.46    30.9 1952.74    36.1 1951.68
    39.9 1950.26    44.2 1947.73    46.5 1946.77    48.6 1946.15    57.1 1945.91
    61.5 1946.18    65.9 1946.88    70.2  1947.8    78.9 1947.84    83.2  1948.3
    90.8 1950.53    98.8 1953.48   104.8 1954.79   108.8 1955.08   117.9 1954.91
   132.7 1955.37   144.9 1955.23     153 1956.07     161 1956.22   172.6 1957.56
   193.2 1957.78   197.2 1958.04   205.2 1959.23   209.3 1959.59   226.1 1960.13
#Mann= 3 ,-1,0
       0      .1       0    46.5    .045       0    65.9      .1       0
Bank Sta=46.5,65.9
XS Rating Curve= 0 ,0
Exp/Cntr(USF)=0,0
Exp/Cntr=0.3,0.1

Type RM Length L Ch R = 1 ,4636    ,110.8,109.7,109.5
XS GIS Cut Line= 4
2171978.14872271646743.4784687862172068.19811662646810.090349213
2172129.05341478646808.8567958722172203.88898415646832.294309355
#Sta/Elev= 30
       0 1970.62     8.4 1966.14      17 1961.09    22.4  1958.2    37.3 1951.11
    42.3 1948.91    48.4 1945.66    49.9 1945.08    52.3 1944.52    62.7 1944.22
    68.4 1944.61    72.2 1945.77    76.8 1948.42    82.1 1949.93    87.1 1949.94
    92.1 1950.82   102.8 1951.73     112 1953.45     116 1953.45     124 1952.63
     128 1952.49     156 1952.62   176.1 1953.31     198 1952.59   213.9 1952.94
   227.5 1952.51   230.6 1952.69   233.1 1953.11   242.7 1955.18   251.3 1957.96
#Mann= 3 ,-1,0
       0      .1       0    48.4    .045       0    72.2      .1       0
Bank Sta=48.4,72.2
XS Rating Curve= 0 ,0
Exp/Cntr(USF)=0,0
Exp/Cntr=0.3,0.1

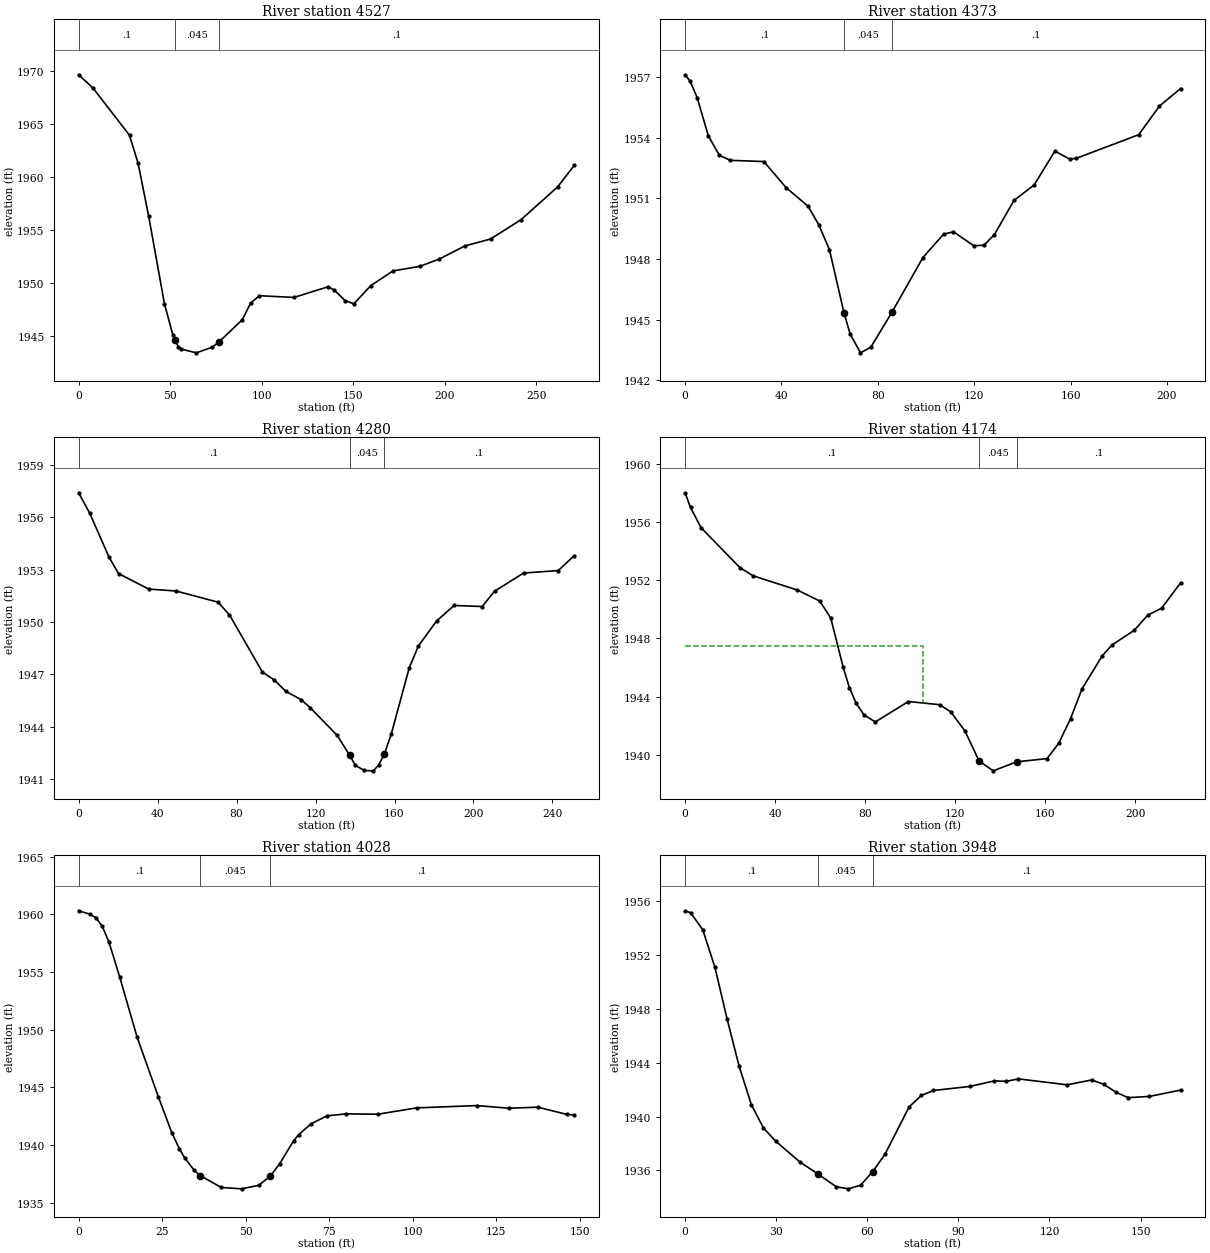
Type RM Length L Ch R = 1 ,4527    ,157.3,154.1,152.8
XS GIS Cut Line= 4
2171917.58197393646813.3649229952171916.10170992646836.309015142
2171993.81557041646885.5277934582172127.30540635646965.846639286
#Sta/Elev= 30
       0 1969.62     7.8 1968.38    27.8 1963.91    32.5 1961.26    38.2 1956.34
    46.9 1948.01    51.5 1945.06    52.7 1944.55    54.5 1943.97    56.2 1943.73
    64.3 1943.38      73 1943.91    76.9 1944.44    89.4  1946.5    94.1  1948.1
    98.8 1948.77   117.7 1948.61   136.4 1949.62   139.8 1949.29   145.6 1948.31
   150.4 1948.01   159.7 1949.73   171.8 1951.11   186.4 1951.54   197.1 1952.23
   211.1 1953.47   225.1 1954.12   241.8 1955.95   261.7 1959.03   270.8 1961.06
#Mann= 3 ,-1,0
       0      .1       0    52.7    .045       0    76.9      .1       0
Bank Sta=52.7,76.9
XS Rating Curve= 0 ,0
Exp/Cntr(USF)=0,0
Exp/Cntr=0.3,0.1

Type RM Length L Ch R = 1 ,4373    ,89.1,92.2,92.8
XS GIS Cut Line= 5
2171851.87417187646968.1520633382171898.13242216646994.796815509
2171945.87093647647014.0402476322171990.64892276 647027.73268972
2172035.05684304647058.448167917
#Sta/Elev= 30
       0 1957.13     2.1 1956.81       5    1956     9.6 1954.12    14.2 1953.14
    18.8 1952.89    32.7 1952.83    41.9 1951.54    51.1 1950.61    55.6 1949.67
    59.9 1948.47      66 1945.31    68.5 1944.29    72.8 1943.35    77.1 1943.63
    85.8 1945.35    98.7 1948.07   107.3 1949.23   111.4 1949.35   119.8 1948.66
     124 1948.68   128.4 1949.21   136.5  1950.9   144.9 1951.67   153.5 1953.35
   159.6 1952.95   162.4 1952.99   188.3 1954.16   196.9 1955.58   205.7 1956.45
#Mann= 3 ,-1,0
       0      .1       0      66    .045       0    85.8      .1       0
Bank Sta=66,85.8
XS Rating Curve= 0 ,0
Exp/Cntr(USF)=0,0
Exp/Cntr=0.3,0.1

Type RM Length L Ch R = 1 ,4280    ,100,106.6,109.8
XS GIS Cut Line= 5
2171819.44542514646984.5344639262171850.53096934647029.682516215
2171857.19215738647065.2088524432171925.28430182647102.955584685
2171996.70704028647143.662844946
#Sta/Elev= 30
       0 1957.41     5.6 1956.24    15.4 1953.72    20.2 1952.78    35.5 1951.89
    49.3 1951.78    70.6 1951.14    76.4 1950.41    93.1 1947.13    99.1 1946.68
   104.9 1946.03   112.7 1945.55   117.2  1945.1     131  1943.5   137.3 1942.36
   140.2 1941.78   144.7 1941.49   149.3 1941.47     152 1941.81   154.9 1942.44
   158.4  1943.6   167.5 1947.39   172.1 1948.63   181.3 1950.06   190.2 1950.95
   204.4 1950.89   210.7 1951.77   225.4 1952.81   242.9 1952.95     251  1953.8
#Mann= 3 ,-1,0
       0      .1       0   137.3    .045       0   154.9      .1       0
Bank Sta=137.3,154.9
XS Rating Curve= 0 ,0
Exp/Cntr(USF)=0,0
Exp/Cntr=0.3,0.1

Type RM Length L Ch R = 1 ,4174    ,146.9,146,145
XS GIS Cut Line= 4
2171738.77102192647028.6545632672171800.94212502647115.167762764
2171847.57044132647172.1579271292171883.83690955647188.810897236
#Sta/Elev= 30
       0    1958     2.4 1956.99     7.1  1955.6    24.3 1952.87    30.2  1952.3
    49.9 1951.32    59.8 1950.57    64.7  1949.4    70.2 1946.03      73 1944.61
    75.9 1943.57    79.5 1942.74    84.5 1942.27    99.2 1943.67   113.1 1943.45
     118 1942.96   124.3 1941.65   130.6 1939.58   136.9 1938.91   147.2 1939.53
   160.8 1939.75     166 1940.82   171.2 1942.49   176.3 1944.54   185.2 1946.79
   189.6 1947.55   199.5 1948.56   205.5  1949.6   211.6 1950.07   220.1 1951.82
#Mann= 3 ,-1,0
       0      .1       0   130.6    .045       0   147.2      .1       0
#XS Ineff= 2 , 0
          105.63  1947.5
Permanent Ineff=
       F       F
Bank Sta=130.6,147.2
XS Rating Curve= 0 ,0
Exp/Cntr(USF)=0,0
Exp/Cntr=0.3,0.1

Type RM Length L Ch R = 1 ,4028    ,87.4,79.3,70.4
XS GIS Cut Line= 3
 2171652.8422827647131.7244968662171705.83938921 647195.22965036
2171766.14644145647221.271332008
#Sta/Elev= 30
       0  1960.3     3.4    1960     5.2 1959.69     7.1 1958.94     9.1 1957.57
    12.3 1954.56    17.5 1949.35    23.9 1944.15    27.9 1941.06    30.2 1939.64
    31.8 1938.86    34.6  1937.8    36.4 1937.34    42.7 1936.31    48.8 1936.19
      54  1936.5    57.4  1937.3    60.2 1938.36    64.4 1940.37    65.9 1940.89
    69.6 1941.83    74.4 1942.52    80.1 1942.69    89.6 1942.66   101.2 1943.21
   119.4 1943.41   128.8 1943.18   137.5 1943.27   146.3 1942.64   148.4  1942.6
#Mann= 3 ,-1,0
       0      .1       0    36.4    .045       0    57.4      .1       0
Bank Sta=36.4,57.4
XS Rating Curve= 0 ,0
Exp/Cntr(USF)=0,0
Exp/Cntr=0.3,0.1

Type RM Length L Ch R = 1 ,3948    ,126.2,119.3,108.9
XS GIS Cut Line= 3
2171610.35322317647239.5461963232171679.34083596647239.089324715
2171773.45638718 647235.89122346
#Sta/Elev= 30
       0 1955.25     1.8 1955.11     5.8 1953.85     9.8 1951.08    13.8 1947.26
    17.8 1943.72    21.8 1940.89    25.8 1939.15    29.8 1938.18    37.8 1936.63
    43.7 1935.75    49.8 1934.79    53.8 1934.64    57.8 1934.91    61.8 1935.92
    65.8 1937.19    73.8 1940.72    77.8 1941.56    81.8 1941.93    93.8 1942.23
   101.8 1942.64   105.8 1942.61   109.8 1942.79   125.8 1942.35   133.9 1942.71
   137.9 1942.39   141.9  1941.8   145.9  1941.4   152.9 1941.49   163.2 1941.96
#Mann= 3 ,-1,0
       0      .1       0    43.7    .045       0    61.8      .1       0
Bank Sta=43.7,61.8
XS Rating Curve= 0 ,0
Exp/Cntr(USF)=0,0
Exp/Cntr=0.3,0.1

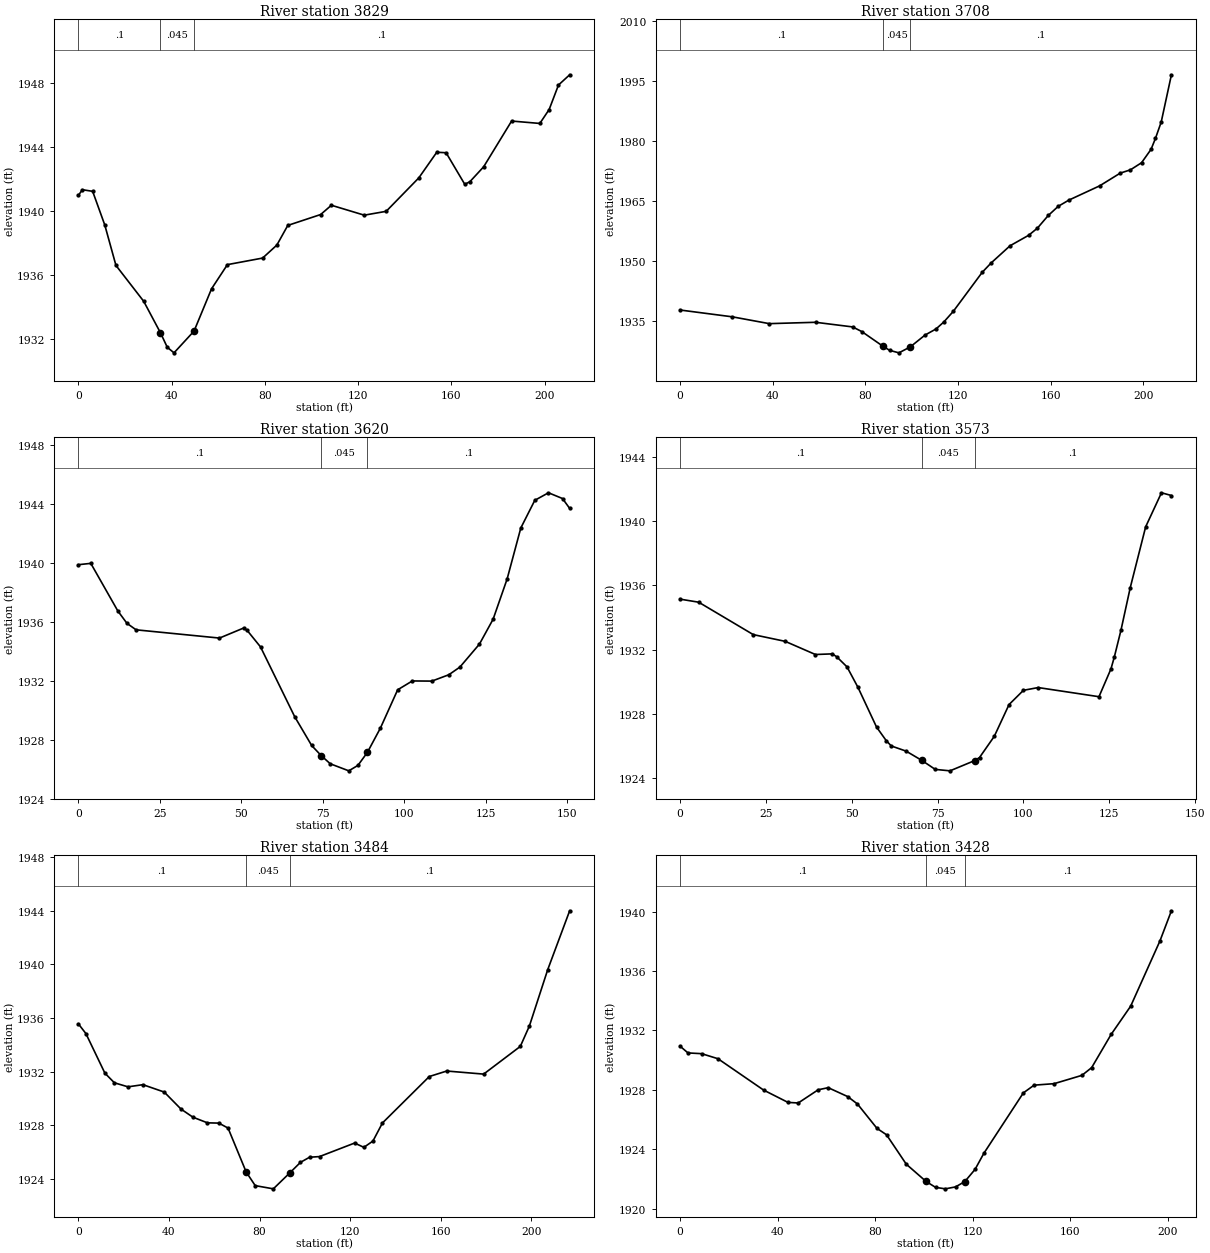
Type RM Length L Ch R = 1 ,3829    ,110.9,121.2,128.7
XS GIS Cut Line= 4
2171676.82522192 647374.620005172171722.46669554647305.129833613
2171773.86475143647273.879815635 2171840.8878163647266.889680034
#Sta/Elev= 30
       0 1940.96     1.7 1941.31     6.1 1941.21    11.3 1939.11    16.1 1936.58
      28 1934.34    35.2 1932.37    38.1 1931.47      41 1931.12    49.6 1932.48
    57.1 1935.12    63.9 1936.63      79 1937.04    85.1 1937.85    89.8 1939.08
   103.9 1939.76   108.5 1940.34   122.6 1939.72     132 1939.96     146 1942.05
   153.7 1943.65   157.7 1943.62   165.7 1941.65   167.9 1941.81   173.8 1942.74
   185.8  1945.6   197.9 1945.45   201.9 1946.32   205.9 1947.85   210.7 1948.49
#Mann= 3 ,-1,0
       0      .1       0    35.2    .045       0    49.6      .1       0
Bank Sta=35.2,49.6
XS Rating Curve= 0 ,0
Exp/Cntr(USF)=0,0
Exp/Cntr=0.3,0.1

Type RM Length L Ch R = 1 ,3708    ,81.3,87.8,93.5
XS GIS Cut Line= 3
2171697.66991678647402.5295975742171851.63564863647405.270827221
2171904.17588354647430.398765654
#Sta/Elev= 30
       0 1937.69    22.5 1935.99    38.5 1934.28    58.5 1934.62    74.5 1933.46
    78.5 1932.28    87.6 1928.62    90.5 1927.59    94.5 1926.97    99.4 1928.46
   105.8 1931.43   110.5 1932.94   113.9  1934.7     118 1937.37   130.5 1947.15
   134.3 1949.46   142.5 1953.78   150.5 1956.39   154.3 1958.18     159 1961.36
   163.3 1963.65   167.9 1965.21   181.2 1968.78   190.1 1971.97   194.5 1972.79
   199.3 1974.57   203.4 1977.92   205.3 1980.65   207.8 1984.78   212.2 1996.59
#Mann= 3 ,-1,0
       0      .1       0    87.6    .045       0    99.4      .1       0
Bank Sta=87.6,99.4
XS Rating Curve= 0 ,0
Exp/Cntr(USF)=0,0
Exp/Cntr=0.3,0.1

Type RM Length L Ch R = 1 ,3620    ,50.3,47.5,44.1
XS GIS Cut Line= 3
2171681.60631105647418.7256960732171771.53234963647495.329358564
2171802.24782782647506.431338636
#Sta/Elev= 30
       0 1939.87     3.8 1939.96    12.1 1936.73    14.9 1935.89    17.7 1935.45
    43.3 1934.89    50.7 1935.57    51.8 1935.41    55.9 1934.29    66.4 1929.55
    71.6  1927.6    74.5 1926.92    77.3 1926.36      83 1925.88    85.8 1926.25
    88.7 1927.13    92.7 1928.78      98 1931.38   102.5 1931.98   108.5 1931.97
   113.7  1932.4   117.1 1932.92   123.1 1934.48   127.3 1936.17   131.6  1938.9
   135.8 1942.36   140.1 1944.24   144.3 1944.75   148.6 1944.36   150.8 1943.69
#Mann= 3 ,-1,0
       0      .1       0    74.5    .045       0    88.7      .1       0
Bank Sta=74.5,88.7
XS Rating Curve= 0 ,0
Exp/Cntr(USF)=0,0
Exp/Cntr=0.3,0.1

Type RM Length L Ch R = 1 ,3573    ,92,89,87
XS GIS Cut Line= 4
2171665.64677052647462.3893668692171684.56125508647498.162413765
 2171751.9955044647524.0670339312171778.72249347647538.458489578
#Sta/Elev= 30
       0 1935.14     5.4 1934.95    21.3 1932.93    30.6 1932.51    39.4 1931.69
    44.3 1931.73    45.6 1931.55    48.6 1930.92    51.8 1929.64    57.2 1927.17
      60 1926.33    61.5 1925.99    65.8 1925.67    70.4 1925.09    74.3 1924.53
    78.6 1924.44    85.8 1925.08    87.2 1925.27    91.5 1926.59    95.8 1928.57
     100 1929.46   104.3 1929.63     122 1929.06   125.5  1930.8   126.5 1931.56
   128.4  1933.2   131.1 1935.85   135.6 1939.65   140.2 1941.77   143.1  1941.6
#Mann= 3 ,-1,0
       0      .1       0    70.4    .045       0    85.8      .1       0
Bank Sta=70.4,85.8
XS Rating Curve= 0 ,0
Exp/Cntr(USF)=0,0
Exp/Cntr=0.3,0.1

Type RM Length L Ch R = 1 ,3484    ,54.4,55.4,58.9
XS GIS Cut Line= 5
2171601.03610054647572.7671219612171660.61672692647591.640488082
 2171735.7401254647593.4908180942171778.29771568647602.742468153
2171813.82405191647607.553326184
#Sta/Elev= 30
       0 1935.56     3.3 1934.84    11.7 1931.88    15.9 1931.16    21.9 1930.86
    28.5 1931.02    37.9 1930.47    45.3  1929.2    50.6 1928.59      57 1928.17
      62 1928.15    66.1 1927.78    74.1  1924.5    78.1 1923.48    86.1 1923.24
    93.3 1924.42    98.1 1925.22   102.1  1925.6   106.5 1925.65     122 1926.66
   126.1 1926.34   130.1 1926.81   134.3 1928.16     155 1931.63   162.7 1932.04
     179 1931.81   195.2 1933.88   199.2  1935.4   207.3 1939.61     217 1944.01
#Mann= 3 ,-1,0
       0      .1       0    74.1    .045       0    93.3      .1       0
Bank Sta=74.1,93.3
XS Rating Curve= 0 ,0
Exp/Cntr(USF)=0,0
Exp/Cntr=0.3,0.1

Type RM Length L Ch R = 1 ,3428    ,53.9,54.3,56.3
XS GIS Cut Line= 4
2171601.03610054 647627.166824312171659.50652892647640.859266398
2171745.36184147647641.5993984032171800.87174182 647642.70959641
#Sta/Elev= 30
       0 1930.94     3.2 1930.49     8.8 1930.44    15.5  1930.1    34.2 1927.99
    44.2 1927.16    48.4 1927.12    56.6 1928.01    60.7 1928.15    68.7 1927.55
    72.7 1927.05    80.7 1925.41    84.6 1924.98    92.7    1923   100.8 1921.84
   104.7 1921.44   108.7 1921.34   112.9 1921.47   116.7 1921.83   120.9 1922.65
   124.5 1923.73   140.7  1927.8   145.1 1928.32   153.3 1928.42   164.7 1928.98
   168.7  1929.5   176.7 1931.74   184.7 1933.64   196.7 1938.03   201.4 1940.06
#Mann= 3 ,-1,0
       0      .1       0   100.8    .045       0   116.7      .1       0
Bank Sta=100.8,116.7
XS Rating Curve= 0 ,0
Exp/Cntr(USF)=0,0
Exp/Cntr=0.3,0.1