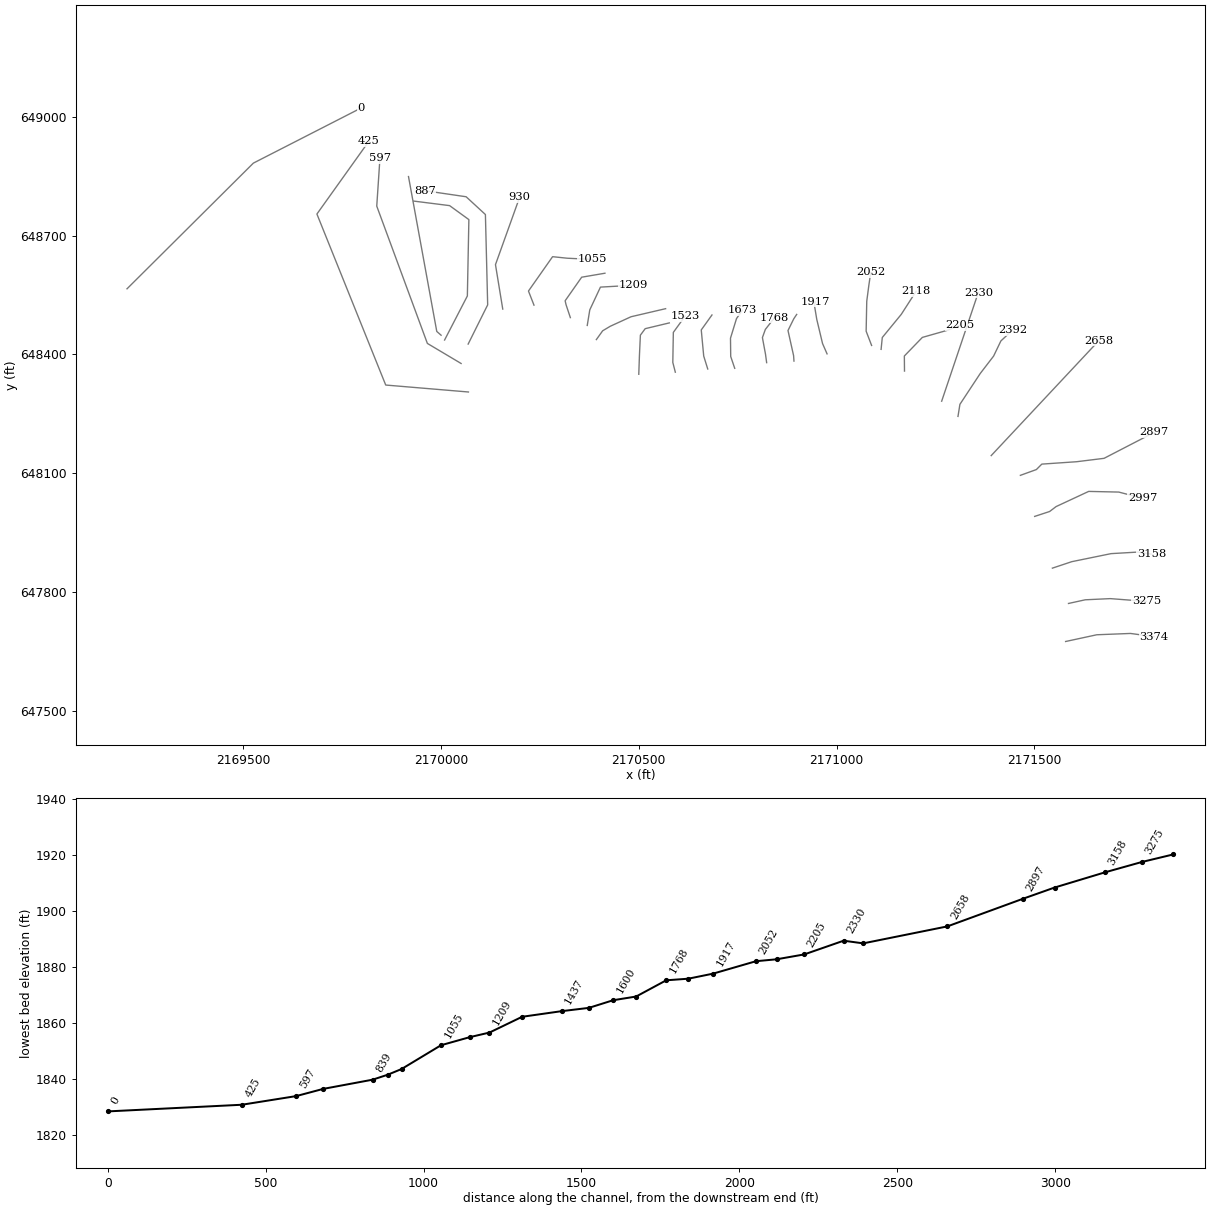
HEC-RAS study GETOUTRN.prj: GETOUTRN

--- GETOUTRN.g01 (geometry) --- (continued)

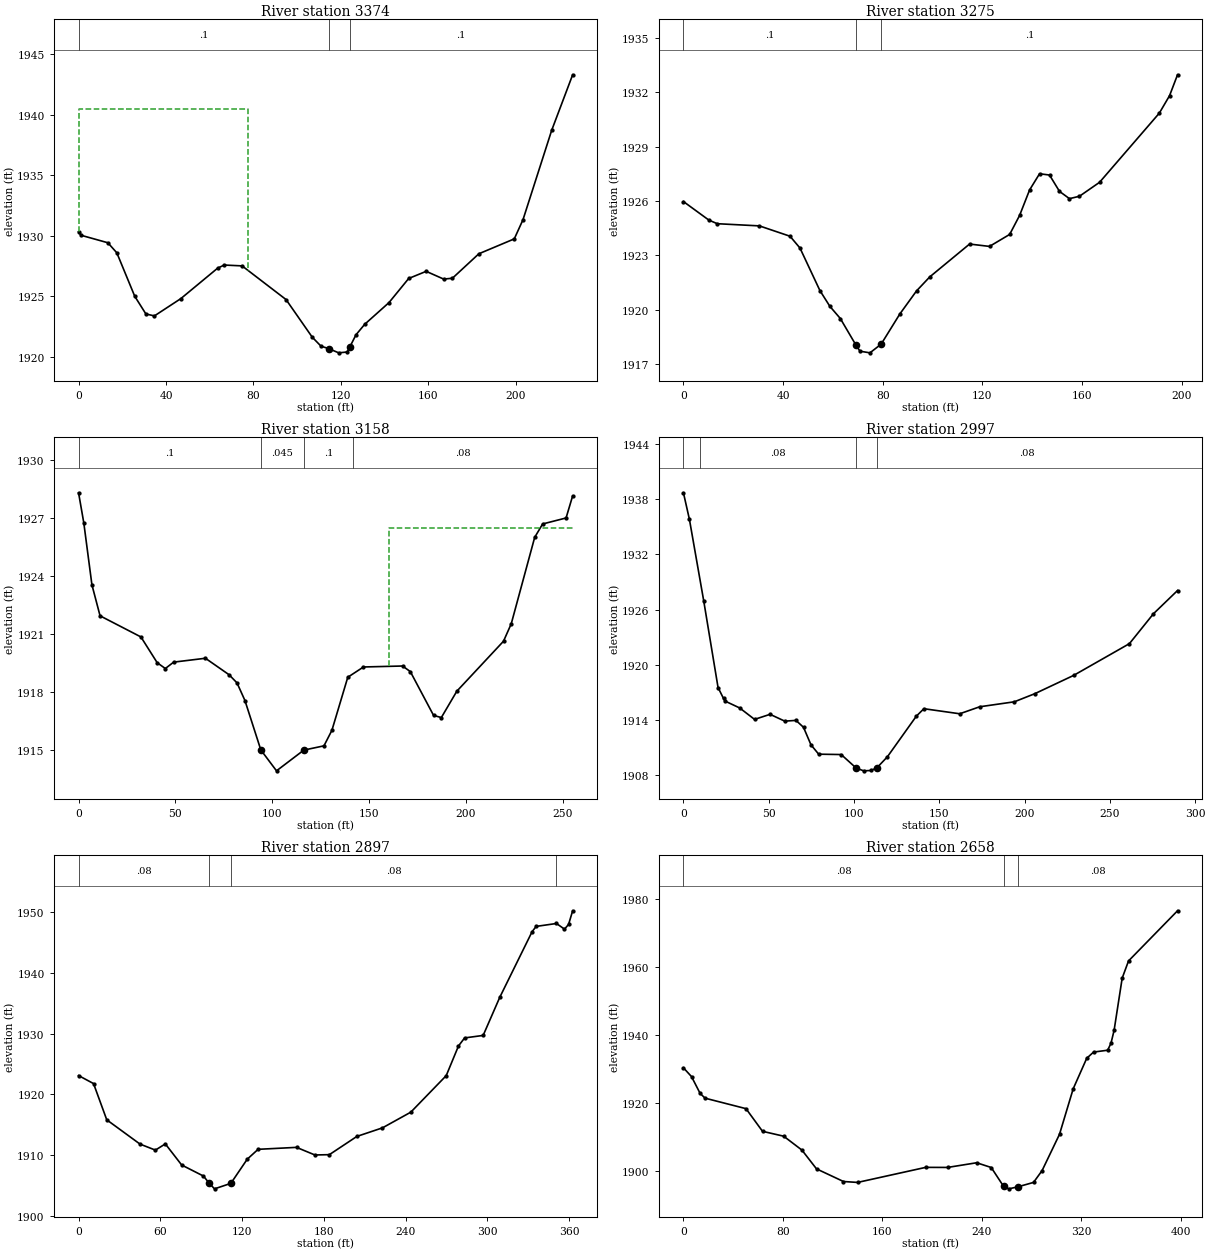
Type RM Length L Ch R = 1 ,3374    ,98,99.4,98.3
XS GIS Cut Line= 4
2171579.08392742647674.6789333532171657.90798592647691.701969462
2171743.02316647647695.0325634832171802.60379285647686.891111431
#Sta/Elev= 30
       0 1930.34     1.1 1930.05    13.4 1929.43    17.5  1928.6    25.7 1925.01
    30.8 1923.55    34.7 1923.39    46.8 1924.82    63.6 1927.33    66.6 1927.59
    74.8 1927.52    94.9 1924.74   106.9 1921.63   110.9 1920.89   114.41920.689
     119 1920.34   122.9 1920.41   124.11920.836   126.9 1921.83   130.9  1922.7
     142 1924.49     151 1926.48     159 1927.07     167 1926.43     171  1926.5
   183.1 1928.52   199.3 1929.75   203.3 1931.34   216.4 1938.71     226  1943.3
#Mann= 3 ,-1,0
       0      .1       0   114.4    .045       0   124.1      .1       0
#XS Ineff= 2 , 0
           77.61 1940.51
Permanent Ineff=
       F       F
Bank Sta=114.4,124.1
XS Rating Curve= 0 ,0
Exp/Cntr(USF)=0,0
Exp/Cntr=0.3,0.1

Type RM Length L Ch R = 1 ,3275    ,109.5,116.9,116
XS GIS Cut Line= 4
2171586.35764319647770.7970264342171628.70603487647780.079695854
2171691.98732128647783.0402238732171783.39362387647776.008969828
#Sta/Elev= 30
       0 1925.97    10.2 1924.95    13.6 1924.75    30.5 1924.63    42.8 1924.06
    46.8 1923.41    54.8 1921.07    58.8  1920.2      63 1919.53    69.21918.083
    70.9 1917.73    74.9 1917.64    79.4 1918.12    86.9 1919.78    93.6 1921.05
    98.9 1921.82   114.9 1923.63   122.9  1923.5     131 1924.16     135 1925.21
     139 1926.61     143  1927.5     147 1927.43     151 1926.53     155 1926.13
     159 1926.26   167.1 1927.03   191.1 1930.84   195.2  1931.8   198.4 1932.95
#Mann= 3 ,-1,0
       0      .1       0    69.2    .045       0    79.4      .1       0
Bank Sta=69.2,79.4
XS Rating Curve= 0 ,0
Exp/Cntr(USF)=0,0
Exp/Cntr=0.3,0.1

Type RM Length L Ch R = 1 ,3158    ,157,160.2,162
XS GIS Cut Line= 5
2171545.63773964647860.0567819622171594.70913456647876.413913601
2171693.98000244647896.7193183952171761.66468509 647900.66759155
2171795.50702641647895.591240351
#Sta/Elev= 30
       0 1928.29     2.7 1926.74     6.9 1923.54    11.1 1921.94    32.2 1920.85
    40.6 1919.52    44.8 1919.22    49.1 1919.55    65.5 1919.75    77.7  1918.9
    81.8 1918.48    85.9 1917.57    94.1 1915.02   102.2 1913.94   116.3 1915.01
   126.7 1915.23   130.8 1916.03     139 1918.77   147.1  1919.3   167.3 1919.35
   171.3 1919.06   183.3  1916.8   187.3 1916.69   195.3 1918.05   219.4 1920.63
   223.4 1921.53   235.5 1925.99   239.6 1926.68   251.7 1926.99   255.1 1928.13
#Mann= 4 ,-1,0
       0      .1       0    94.1    .045       0   116.3      .1       0
  141.73     .08       0
#XS Ineff= 2 , 0
                          160.06         1926.45
Permanent Ineff=
       F       F
Bank Sta=94.1,116.3
XS Rating Curve= 0 ,0
Exp/Cntr(USF)=0,0
Exp/Cntr=0.3,0.1

Type RM Length L Ch R = 1 ,2997    ,103.8,100.2,96.4
XS GIS Cut Line= 6
2171500.85124168 647990.792762842171538.64185616648003.201621326
 2171554.9989878648015.6104798112171637.34868502648053.965133311
  2171713.493953648052.2730162452171773.84612836648036.479923627
#Sta/Elev= 30
       0 1938.69     3.5 1935.81    11.9 1926.94    20.3 1917.53    23.5 1916.34
    24.5 1916.05      33 1915.31    41.7 1914.07    50.8 1914.62    59.4 1913.88
      66 1913.96    70.4 1913.21    74.8  1911.3    79.3 1910.29    92.5 1910.25
   101.3 1908.78   105.7 1908.48   110.1 1908.52   113.6 1908.84   119.6 1910.01
   136.6 1914.43     141 1915.23     162 1914.68   173.7 1915.44     194 1915.98
     206 1916.86   228.8 1918.85   261.5  1922.3   275.6 1925.55   289.7 1928.07
#Mann= 4 ,-1,0
       0      .1       0      10     .08       0   101.3    .045       0
   113.6     .08       0
Bank Sta=101.3,113.6
XS Rating Curve= 0 ,0
Exp/Cntr(USF)=0,0
Exp/Cntr=0.3,0.1

Type RM Length L Ch R = 1 ,2897    ,228.3,238.8,242.8
XS GIS Cut Line= 6
2171464.75581059648094.5646967162171505.16098364648109.179333775
2171518.91593617648122.9342863022171606.60375853648128.952078033
 2171676.2382057648137.5489233622171802.61183204648202.884947865
#Sta/Elev= 30
       0  1923.1      11 1921.78    20.7 1915.82    45.1 1911.83    56.4 1910.84
    63.7 1911.86    75.7 1908.39    91.7 1906.57    95.7 1905.45    99.8 1904.47
   111.8 1905.37   123.8 1909.34   131.8 1910.97     160 1911.29   173.5 1910.04
   184.1 1910.09   204.3 1913.09   223.1  1914.5   243.9 1917.08   269.9 1923.09
   278.9 1927.97   283.4 1929.29     297  1929.7   309.2 1935.97   332.9 1946.75
   335.9 1947.63   350.8 1948.11   356.7 1947.18   359.7 1947.95   362.7  1950.2
#Mann= 4 ,-1,0
       0     .08       0    95.7    .045       0   111.8     .08       0
  350.48     .05       0
Bank Sta=95.7,111.8
XS Rating Curve= 0 ,0
Exp/Cntr(USF)=0,0
Exp/Cntr=0.3,0.1

Type RM Length L Ch R = 1 ,2658    ,262.9,266.5,267.8
XS GIS Cut Line= 2
2171390.99784864648144.4574458122171662.55829498 648434.39416296
#Sta/Elev= 30
       0 1930.29     6.5  1927.7    13.4 1922.76    17.4 1921.34    50.3 1918.25
    63.6 1911.57    80.6 1910.13    95.3 1906.03     107  1900.5   128.7 1896.77
     140  1896.5   194.8 1900.94   212.4 1900.92   235.8  1902.3   247.5  1900.9
  257.39 1895.37   261.7 1894.61   269.31895.247   281.5  1896.5   288.4 1899.99
   302.4 1910.69   313.4  1924.1   324.3 1933.11   329.8 1934.93   341.1 1935.48
   343.8 1937.54   346.3 1941.34   352.8 1956.73   357.9  1961.8   397.3 1976.59
#Mann= 3 ,-1,0
       0     .08       0  257.39    .045       0   269.3     .08       0
Bank Sta=257.39,269.3
XS Rating Curve= 0 ,0
Exp/Cntr(USF)=0,0
Exp/Cntr=0.3,0.1

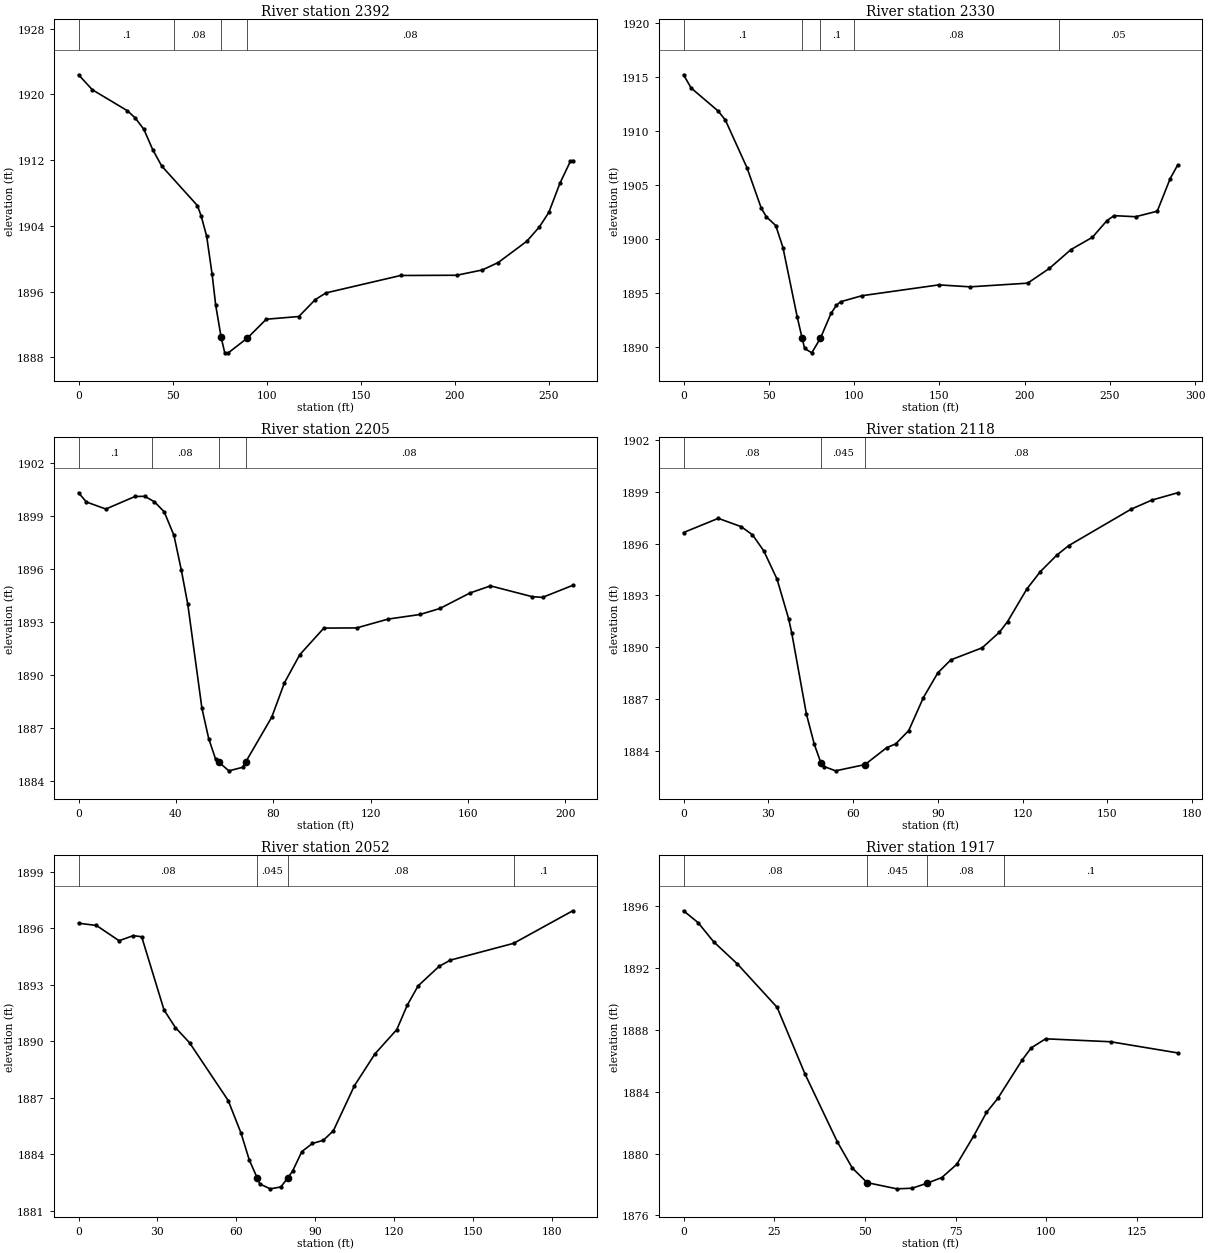
Type RM Length L Ch R = 1 ,2392    ,59.5,62.1,64.7
XS GIS Cut Line= 6
2171307.02391734648243.4970301152171311.88103897648273.993122992
 2171363.2897478648351.9494244022171397.08854238648395.968247741
2171415.42621752648434.1507236672171445.09933113648461.846068522
#Sta/Elev= 30
       0 1922.37     7.3 1920.55      26 1917.99    30.1 1917.12    34.7 1915.74
    39.4 1913.27    44.2 1911.27    63.2 1906.45    65.2 1905.17    68.1 1902.72
      71 1898.09    72.9 1894.34    75.81890.423    77.7 1888.56    79.6 1888.54
    89.8 1890.35    99.8 1892.63   117.1 1892.96   125.8 1895.01   131.5 1895.83
   171.2 1897.95     201 1897.98   214.6 1898.62   223.1 1899.53   238.3 1902.12
     245 1903.87     250 1905.63   255.9 1909.18   261.4 1911.82   262.7 1911.94
#Mann= 4 ,-1,0
       0      .1       0   50.88     .08       0    75.8    .045       0
    89.8     .08       0
Bank Sta=75.8,89.8
XS Rating Curve= 0 ,0
Exp/Cntr(USF)=0,0
Exp/Cntr=0.3,0.1

Type RM Length L Ch R = 1 ,2330    ,128.1,124.6,118.9
XS GIS Cut Line= 2
2171265.76696611 648281.939175542171358.39780472648556.539767196
#Sta/Elev= 30
       0 1915.23     4.5    1914    20.2 1911.89    24.5 1911.05    37.2 1906.63
    45.6 1902.88    48.6 1902.08    54.1 1901.27    58.3 1899.24    66.7 1892.79
    69.51890.886      71  1889.9    75.2 1889.49    80.2 1890.82    86.5 1893.14
    89.7  1893.9    92.1 1894.22   104.7 1894.78   149.7 1895.78   168.1  1895.6
   201.8 1895.94   214.5  1897.3   227.2 1899.05   239.8 1900.19   248.3 1901.73
   252.5 1902.19   265.1 1902.09   277.8  1902.6   285.4 1905.62   289.8 1906.88
#Mann= 5 ,-1,0
       0      .1       0    69.5    .045       0    80.2      .1       0
     100     .08       0     220     .05       0
Bank Sta=69.5,80.2
XS Rating Curve= 0 ,0
Exp/Cntr(USF)=0,0
Exp/Cntr=0.3,0.1

Type RM Length L Ch R = 1 ,2205    ,85.5,87.5,87.3
XS GIS Cut Line= 5
2171171.82057279648358.0185002452171171.45050679648396.135298489
2171216.96862508 648443.13368079 2171282.1002415648461.636980908
2171311.70552169648473.479092984
#Sta/Elev= 30
       0 1900.33     3.2 1899.81    11.2 1899.41    23.2 1900.12    27.2 1900.13
    31.2 1899.82    35.2 1899.25    39.2 1897.92    42.2 1895.98    44.9 1894.01
    50.7 1888.13    53.5 1886.41    56.3 1885.26    57.61885.081    61.8 1884.59
    67.4 1884.79    68.71885.094    79.4 1887.63    84.6 1889.57    90.9 1891.16
   100.8 1892.67   114.3 1892.68   127.2 1893.18   140.3 1893.44   148.5 1893.78
   160.9 1894.66   169.3 1895.06   186.4 1894.45   190.7 1894.41   203.1 1895.09
#Mann= 4 ,-1,0
       0      .1       0      30     .08       0    57.6    .045       0
    68.7     .08       0
Bank Sta=57.6,68.7
XS Rating Curve= 0 ,0
Exp/Cntr(USF)=0,0
Exp/Cntr=0.3,0.1

Type RM Length L Ch R = 1 ,2118    ,57.9,65.4,71.6
XS GIS Cut Line= 4
2171112.67714885648412.8932898412171115.67468347648442.868636033
2171163.63523737648501.3205611072171201.10442011 648559.47273272
#Sta/Elev= 30
       0 1896.64    12.3 1897.46    20.4 1896.98    24.4 1896.51    28.4 1895.58
    33.1 1893.94    37.2 1891.65    38.3 1890.83    43.5 1886.13    46.3 1884.38
    48.6 1883.32    49.8  1883.1    53.8 1882.85    64.2 1883.21    71.9 1884.19
    75.1 1884.41    79.7 1885.18    84.9 1887.09      90 1888.52    94.6 1889.27
   105.7 1889.97   111.8 1890.87   114.7 1891.49   121.5 1893.37   126.3 1894.38
   132.1 1895.33   136.3 1895.88   158.4 1897.99   165.8 1898.52   174.9 1898.94
#Mann= 3 ,-1,0
       0     .08       0    48.6    .045       0    64.2     .08       0
Bank Sta=48.6,64.2
XS Rating Curve= 0 ,0
Exp/Cntr(USF)=0,0
Exp/Cntr=0.3,0.1

Type RM Length L Ch R = 1 ,2052    ,130.5,135.7,134.3
XS GIS Cut Line= 5
2171088.67601166648422.8055578642171074.87848991 648458.80704955
2171076.43187625648534.5563792912171081.82211993648575.565642205
2171086.57442921648607.381760968
#Sta/Elev= 30
       0 1896.27     6.8 1896.15    15.4 1895.34    20.8 1895.61      24 1895.55
    32.5 1891.66    36.8 1890.73    42.2 1889.92    56.9 1886.85    61.8 1885.11
    64.9  1883.7    67.91882.748    68.9 1882.42    72.9 1882.16    76.9 1882.26
    79.5 1882.73    81.4 1883.11    84.9 1884.14    88.9 1884.57    93.1 1884.74
    96.9 1885.25   104.9 1887.64   112.7 1889.33     121 1890.62     125 1891.92
   129.1 1892.94   137.1 1893.98   141.4 1894.31   165.4  1895.2   187.9 1896.93
#Mann= 4 ,-1,0
       0     .08       0    67.9    .045       0    79.5     .08       0
  165.68      .1       0
Bank Sta=67.9,79.5
XS Rating Curve= 0 ,0
Exp/Cntr(USF)=0,0
Exp/Cntr=0.3,0.1

Type RM Length L Ch R = 1 ,1917    ,78.5,78.5,77.9
XS GIS Cut Line= 5
2170976.10282868 648401.561046482170964.68103849648427.602728128
2170950.06114704648488.8235235822170944.57868774648521.718279348
2170945.94930256648533.140069545
#Sta/Elev= 22
       0 1895.66       4  1894.9     8.3 1893.66    14.8 1892.24    25.8 1889.43
    33.5 1885.12    42.4 1880.75    46.5 1879.07    50.6 1878.12    58.8 1877.72
      63 1877.76    67.1 1878.08    71.2 1878.45    75.3  1879.3      80 1881.14
    83.5 1882.65    86.6 1883.55    93.3 1886.02    95.8 1886.81    99.8  1887.4
   117.7 1887.21   136.2 1886.49
#Mann= 4 ,-1,0
       0     .08       0    50.6    .045       0    67.1     .08       0
   88.44      .1       0
Bank Sta=50.6,67.1
XS Rating Curve= 0 ,0
Exp/Cntr(USF)=0,0
Exp/Cntr=0.3,0.1

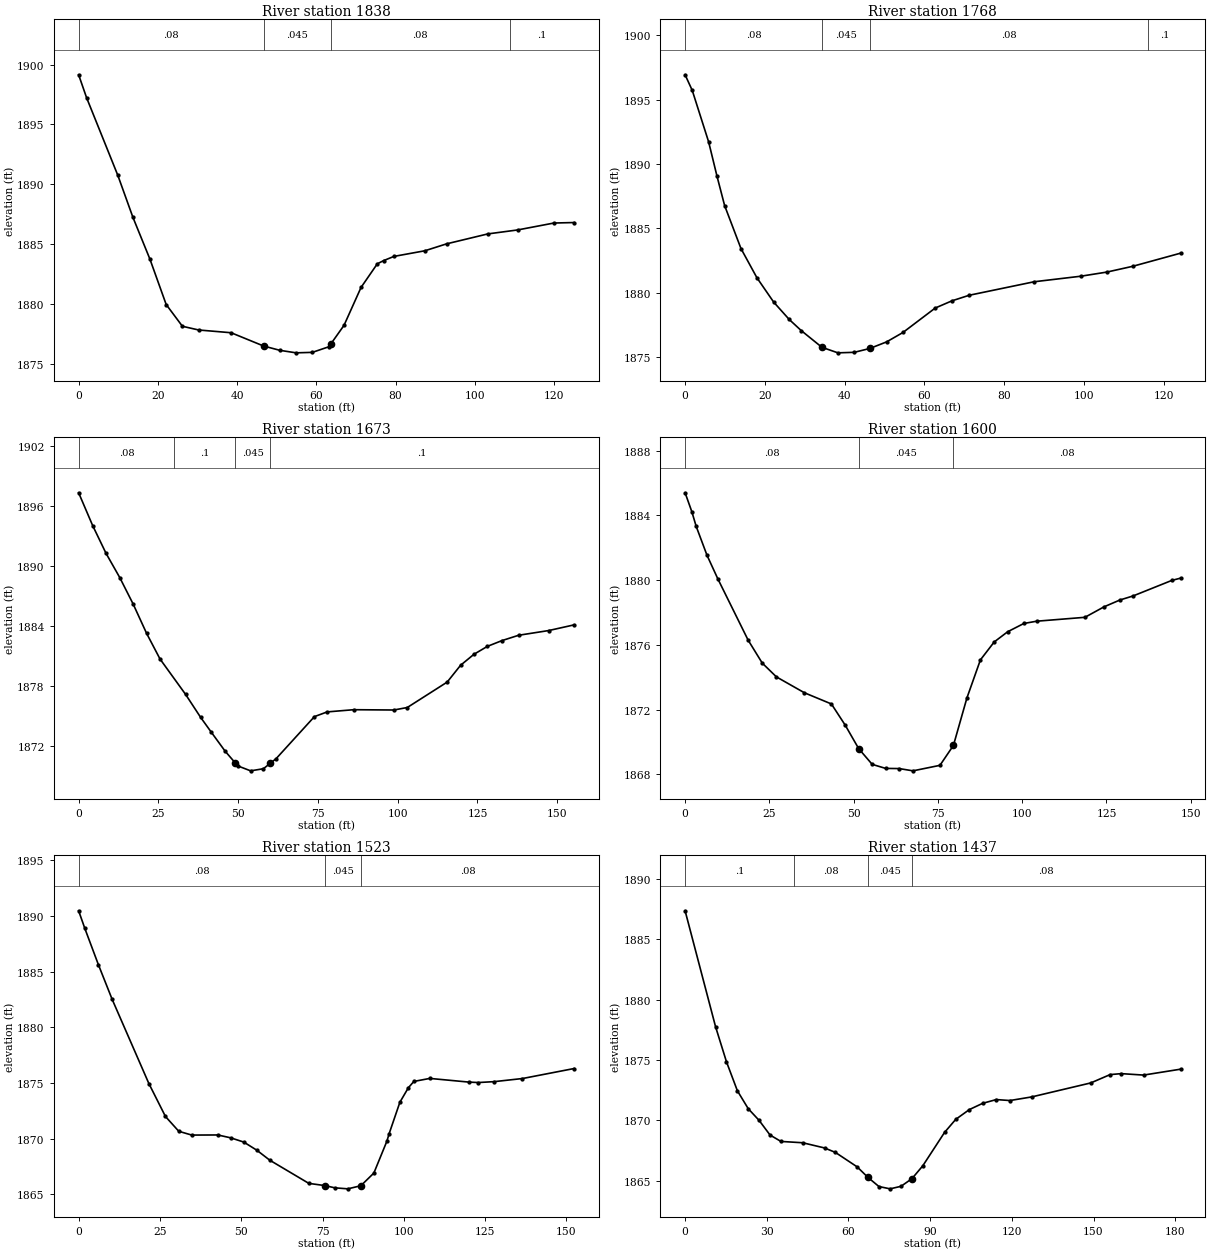
Type RM Length L Ch R = 1 ,1838    ,69.7,69.8,68.8
XS GIS Cut Line= 5
2170892.43892054648383.2861821652170891.52517733648396.992330401
2170877.36215748648460.4974838942170891.98204893648490.194138406
2170899.29199466648501.159056994
#Sta/Elev= 26
       0 1899.15       2 1897.24     9.9 1890.74    13.7 1887.24      18 1883.74
    22.1 1879.95    26.2 1878.13    30.3 1877.82    38.5 1877.59    46.7 1876.48
    50.8 1876.12    54.9 1875.91      59 1875.95    63.1 1876.41    63.6 1876.62
      67 1878.21    71.3 1881.38    75.4 1883.35      77 1883.62    79.6 1883.97
    87.4 1884.44    92.9 1885.02   103.3 1885.85   110.8 1886.18     120 1886.76
   125.1  1886.8
#Mann= 4 ,-1,0
       0     .08       0    46.7    .045       0    63.6     .08       0
   108.8      .1       0
Bank Sta=46.7,63.6
XS Rating Curve= 0 ,0
Exp/Cntr(USF)=0,0
Exp/Cntr=0.3,0.1

Type RM Length L Ch R = 1 ,1768    ,96.4,95.3,93
XS GIS Cut Line= 5
 2170823.3867427648379.3480686772170820.50845157648400.729659925
2170812.69594707648442.6704735272170820.09726712 648463.22969588
 2170843.5347806648493.246160517
#Sta/Elev= 24
       0 1896.93     1.8 1895.71     5.9 1891.72       8 1889.05     9.9 1886.78
      14 1883.44      18 1881.17    22.2 1879.28    26.1 1877.93    29.1 1877.07
    34.31875.769    38.3 1875.34    42.4 1875.38    46.3 1875.68    50.5 1876.19
    54.6 1876.92    62.7 1878.82    66.9 1879.38    71.2 1879.81    87.5 1880.86
    99.2 1881.29   105.7 1881.61   112.2 1882.06   124.2 1883.08
#Mann= 4 ,-1,0
       0     .08       0    34.3    .045       0    46.3     .08       0
  116.09      .1       0
Bank Sta=34.3,46.3
XS Rating Curve= 0 ,0
Exp/Cntr(USF)=0,0
Exp/Cntr=0.3,0.1

Type RM Length L Ch R = 1 ,1673    ,73.2,72.6,73.8
XS GIS Cut Line= 5
2170742.73254678648365.0011721122170732.57984438648394.895240281
2170732.01580536648441.1464400892170747.24485895 648490.78187403
2170761.90987353648511.651317846
#Sta/Elev= 30
       0 1897.33     4.4 1894.05     8.6 1891.27    12.9 1888.85    17.1  1886.2
    21.3 1883.28    25.5 1880.72    33.5 1877.19    38.2  1874.9    41.6 1873.39
    45.9 1871.51    49.11870.326    49.9 1870.03    53.9 1869.54    57.9 1869.75
    60.11870.306    61.9 1870.76    73.9 1874.96    77.9 1875.43    86.2 1875.65
    98.8 1875.62     103 1875.87   115.5 1878.41   119.7 1880.09   123.9 1881.19
   128.1 1881.98   132.7 1882.56   137.9 1883.09   147.3 1883.56   155.3 1884.13
#Mann= 4 ,-1,0
       0     .08       0      30      .1       0    49.1    .045       0
    60.1      .1       0
Bank Sta=49.1,60.1
XS Rating Curve= 0 ,0
Exp/Cntr(USF)=0,0
Exp/Cntr=0.3,0.1

Type RM Length L Ch R = 1 ,1600    ,77.1,77.2,75.1
XS GIS Cut Line= 4
2170674.48382511648363.3090550452170664.33112271648396.023318325
2170658.12669347648462.0158839052170685.20056653648499.806498383
#Sta/Elev= 30
       0 1885.39       2 1884.22     3.3 1883.31     6.5 1881.53     9.7 1880.08
    18.7 1876.29    22.9 1874.87    27.1 1874.02    35.4 1873.04    43.4 1872.35
    47.5 1871.04    51.5 1869.59    55.5 1868.62    59.5 1868.37    63.5 1868.36
    67.6 1868.22    75.6 1868.56    79.6 1869.79    83.6 1872.72    87.6 1875.07
    91.7 1876.18    95.7 1876.81   100.5 1877.32   104.3 1877.46   118.6  1877.7
   124.3 1878.35     129 1878.77   132.9 1879.02   144.4 1879.98     147 1880.12
#Mann= 3 ,-1,0
       0     .08       0    51.5    .045       0    79.6     .08       0
Bank Sta=51.5,79.6
XS Rating Curve= 0 ,0
Exp/Cntr(USF)=0,0
Exp/Cntr=0.3,0.1

Type RM Length L Ch R = 1 ,1523    ,86.2,86,85.4
XS GIS Cut Line= 4
2170592.55629417648355.2287222622170586.22816553 648379.87511802
2170587.56040314648455.8126617062170617.53574933 648497.11202757
#Sta/Elev= 30
       0 1890.46     1.9 1888.88     6.1  1885.6    10.3 1882.51    21.6 1874.94
    26.7 1871.98    30.8 1870.65    34.8 1870.31    42.8 1870.32    46.8 1870.06
    50.8 1869.68    54.8 1868.95    58.8 1868.05    70.8 1865.97    75.8 1865.77
    78.8 1865.57    82.8 1865.48    86.8 1865.76    90.8  1866.9    94.8 1869.76
    95.5 1870.44    98.8 1873.26   101.4 1874.56   103.1 1875.13     108  1875.4
     120 1875.07   122.9 1875.03   127.8 1875.11   136.5 1875.39   152.4 1876.29
#Mann= 3 ,-1,0
       0     .08       0    75.8    .045       0    86.8     .08       0
Bank Sta=75.8,86.8
XS Rating Curve= 0 ,0
Exp/Cntr(USF)=0,0
Exp/Cntr=0.3,0.1

Type RM Length L Ch R = 1 ,1437    ,135.3,125.1,108.9
XS GIS Cut Line= 5
2170500.21662506648349.9876532252170501.83529376 648396.38948913
 2170504.2632968648448.726443581  2170516.403312648465.182908641
2170577.37316616 648479.75092689
#Sta/Elev= 30
       0 1887.36    11.2 1877.74    15.2 1874.84    19.2 1872.44    23.2 1870.95
    27.2 1869.98    31.2 1868.77    35.2 1868.24    43.2 1868.13    51.2  1867.7
    55.2 1867.33    63.2 1866.13    67.2 1865.25    71.2  1864.5    75.3 1864.31
    79.3 1864.52    83.3 1865.15    87.3 1866.22    95.3 1868.99    99.4 1870.07
   104.4 1870.88   109.3  1871.4   114.3 1871.71   119.3 1871.63   127.3 1871.93
     149 1873.09   156.1 1873.78   160.2 1873.86   168.4 1873.74     182 1874.23
#Mann= 4 ,-1,0
       0      .1       0      40     .08       0    67.2    .045       0
    83.3     .08       0
Bank Sta=67.2,83.3
XS Rating Curve= 0 ,0
Exp/Cntr(USF)=0,0
Exp/Cntr=0.3,0.1

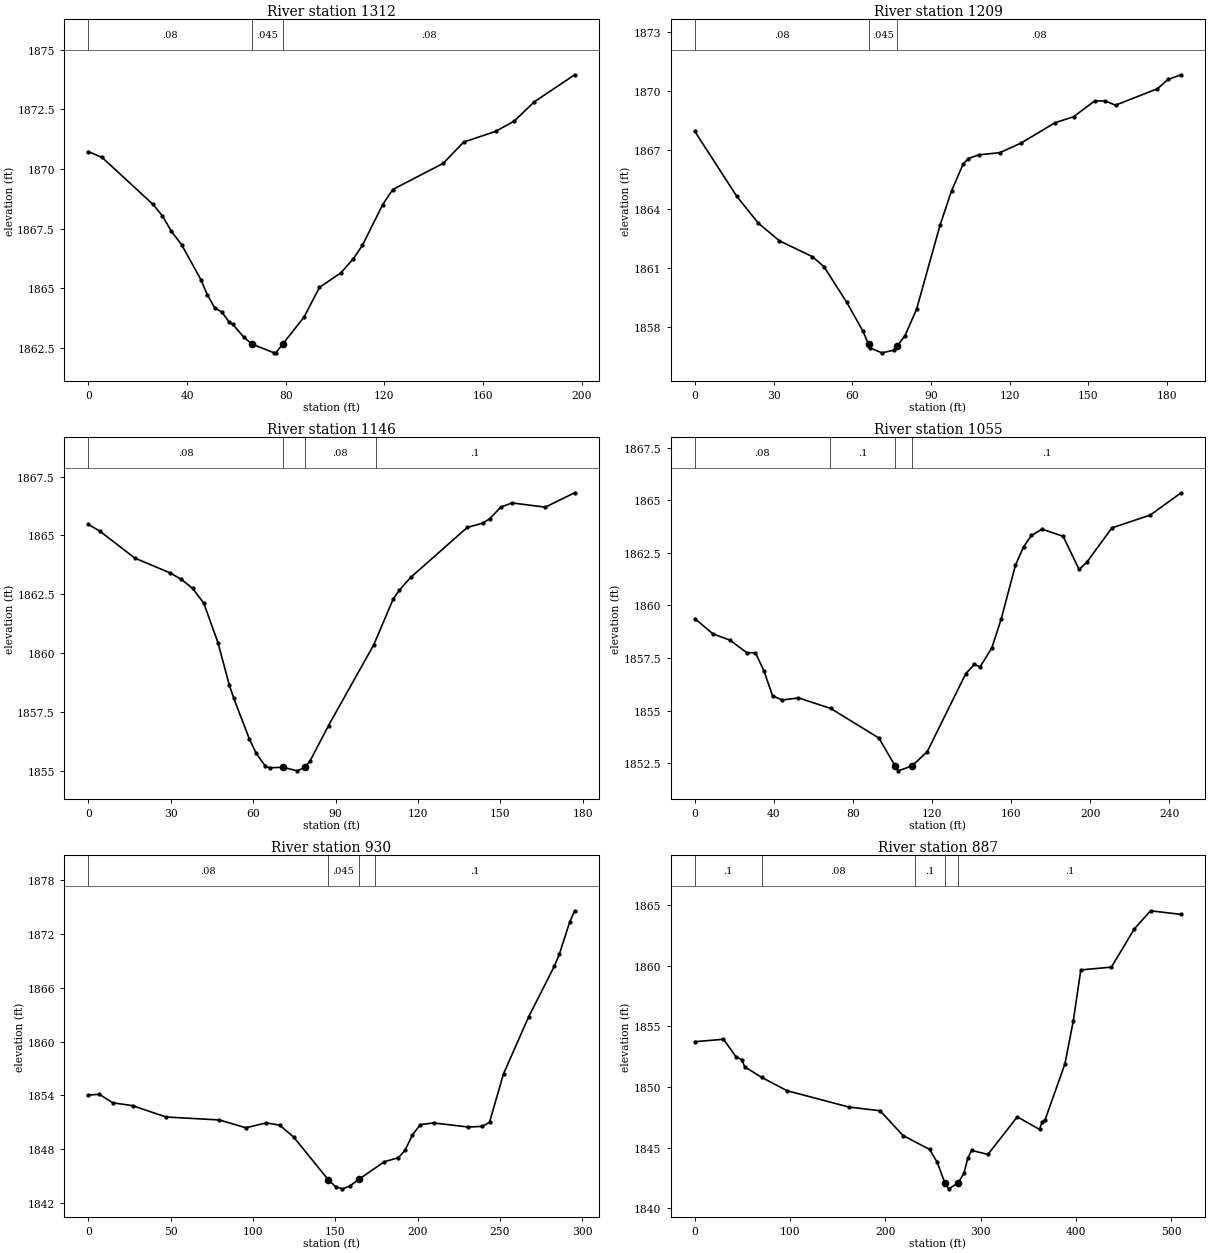
Type RM Length L Ch R = 1 ,1312    ,95.2,103.4,107.3
XS GIS Cut Line= 5
 2170392.9978545 648437.61813127 2170408.9106926648459.822091412
2170428.15412472648471.2941374852170480.70349706648495.348427639
2170568.03907362 648515.70205777
#Sta/Elev= 30
       0 1870.73     5.5 1870.49    26.1 1868.53      30 1868.04    33.6  1867.4
    37.8 1866.83    45.6 1865.37    48.2 1864.74    51.2 1864.19    54.1 1864.01
    57.2 1863.58    58.5  1863.5    62.9 1862.97    66.2 1862.67    75.3  1862.3
    76.1 1862.31    78.91862.679    87.4 1863.79    93.7 1865.04   102.5 1865.66
   107.5 1866.25   111.1  1866.8   119.3  1868.5   123.4 1869.14   143.9 1870.24
   152.2 1871.13   165.2 1871.58   172.7 1872.01   180.9 1872.82   197.2 1873.95
#Mann= 3 ,-1,0
       0     .08       0    66.2    .045       0    78.9     .08       0
Bank Sta=66.2,78.9
XS Rating Curve= 0 ,0
Exp/Cntr(USF)=0,0
Exp/Cntr=0.3,0.1

Type RM Length L Ch R = 1 ,1209    ,63.7,62.3,61.1
XS GIS Cut Line= 4
2170369.97017177648473.3686730082170376.36637428648512.659631285
2170403.32179914648570.2254538762170485.10181695648574.794169954
#Sta/Elev= 30
       0 1867.94      16 1864.63    24.1 1863.28    32.2 1862.37    44.8 1861.56
    49.2 1861.05    57.9 1859.23    64.1 1857.75    66.2 1857.09    66.9  1856.9
    71.3 1856.66    75.7 1856.79    77.1 1857.01    80.1 1857.54    84.5 1858.89
    93.4 1863.15    97.8 1864.91   102.2 1866.27   104.2 1866.56   108.2 1866.75
   116.2 1866.86   124.3 1867.35   137.3 1868.39   144.3 1868.69   152.3 1869.49
   156.3  1869.5   160.3 1869.28   176.3 1870.12   180.3 1870.59   185.3 1870.83
#Mann= 3 ,-1,0
       0     .08       0    66.2    .045       0    77.1     .08       0
Bank Sta=66.2,77.1
XS Rating Curve= 0 ,0
Exp/Cntr(USF)=0,0
Exp/Cntr=0.3,0.1

Type RM Length L Ch R = 1 ,1146    ,91,91.1,91
XS GIS Cut Line= 5
2170327.24233572648493.124522745 2170316.4103106 648525.62059809
2170314.08916236648535.6789071252170355.86983066648595.255045257
2170414.67225272648605.313354293
#Sta/Elev= 30
       0 1865.47     4.3 1865.17    16.9 1864.04    29.6 1863.42    33.8 1863.14
    37.9 1862.76      42 1862.13    47.2 1860.44    51.3 1858.65    52.9  1858.1
    58.6 1856.37    61.1 1855.76    64.4 1855.22      66 1855.15    70.8 1855.17
    76.1 1855.02    78.7 1855.17    80.6 1855.42    87.4 1856.94   103.9 1860.37
   110.9 1862.29   113.2 1862.68   117.3 1863.22   137.9 1865.34   143.5 1865.52
   146.1 1865.71   150.1  1866.2   154.2 1866.38   166.3  1866.2     177 1866.81
#Mann= 4 ,-1,0
       0     .08       0    70.8    .045       0    78.7     .08       0
  104.58      .1       0
Bank Sta=70.8,78.7
XS Rating Curve= 0 ,0
Exp/Cntr(USF)=0,0
Exp/Cntr=0.3,0.1

Type RM Length L Ch R = 1 ,1055    ,121.2,125,126.6
XS GIS Cut Line= 5
 2170235.3262768648524.6589285062170221.39938737648560.298620729
 2170282.3668031648647.0940225932170319.50517492648643.225442195
2170383.72360953648640.130577876
#Sta/Elev= 30
       0 1859.37     9.1 1858.65    17.7 1858.35    26.3 1857.75    30.6 1857.75
    34.9  1856.9    39.3  1855.7    44.2  1855.5    52.4  1855.6    68.7  1855.1
    93.1 1853.69   101.31852.365   102.9 1852.13   109.91852.365   117.6 1853.05
   137.1 1856.76   141.4 1857.19   144.3 1857.08   150.2 1857.97     155 1859.36
   162.2 1861.92   166.3 1862.79   170.3 1863.33   175.6 1863.63   186.3 1863.29
   194.4 1861.71   198.4 1862.07     211 1863.69   230.4  1864.3     246 1865.36
#Mann= 4 ,-1,0
       0     .08       0   68.26      .1       0   101.3    .045       0
   109.9      .1       0
Bank Sta=101.3,109.9
XS Rating Curve= 0 ,0
Exp/Cntr(USF)=0,0
Exp/Cntr=0.3,0.1

Type RM Length L Ch R = 1 ,930     ,37.5,43.5,47.5
XS GIS Cut Line= 3
2170156.38469158648514.7052724052170138.00842077648627.004705103
2170199.26265679648797.835963328
#Sta/Elev= 30
       0 1854.04     6.6 1854.14    14.7 1853.19    26.8 1852.87    47.1 1851.61
    79.5 1851.28    95.7 1850.41   107.9 1850.95   116.1 1850.71   124.6 1849.39
   145.61844.647   150.1 1843.86   154.3 1843.62   158.6 1843.91   164.1 1844.66
   179.7 1846.63   188.3 1847.09   192.3 1847.91   196.8 1849.62   201.6 1850.76
   209.6 1850.95   230.8 1850.49   239.3 1850.57   243.6 1851.03   252.1 1856.41
   267.3 1862.72     283 1868.39   286.1 1869.77   292.3 1873.28   295.3 1874.54
#Mann= 4 ,-1,0
       0     .08       0   145.6    .045       0   164.1     .08       0
  173.79      .1       0
Bank Sta=145.6,164.1
XS Rating Curve= 0 ,0
Exp/Cntr(USF)=0,0
Exp/Cntr=0.3,0.1

Type RM Length L Ch R = 1 ,887     ,51.9,48,48.8
XS GIS Cut Line= 5
2170068.97995036648426.3105715572170118.29686073648525.345329684
2170112.56563051648753.6393334262170063.85017365648798.533970145
2169959.73282466 648813.81725073
#Sta/Elev= 30
       0 1853.74      30 1853.94    43.1 1852.51    49.3 1852.25    52.4 1851.66
      70  1850.8      97 1849.69   161.6 1848.35   194.5 1848.04   218.5    1846
   246.5 1844.85   254.5 1843.78   262.5 1842.08   266.5  1841.6   276.5 1842.09
   282.5 1842.89   286.5 1844.12   290.5 1844.77   307.7 1844.44   338.5 1847.54
   361.9  1846.5   364.4  1847.1   367.8 1847.32   388.5  1851.9   397.3 1855.46
   405.2 1859.66   437.3 1859.89   461.5 1863.06   478.5 1864.54   510.5 1864.24
#Mann= 5 ,-1,0
       0      .1       0      70     .08       0  230.63      .1       0
   262.5    .045       0   276.5      .1       0
Bank Sta=262.5,276.5
XS Rating Curve= 0 ,0
Exp/Cntr(USF)=0,0
Exp/Cntr=0.3,0.1

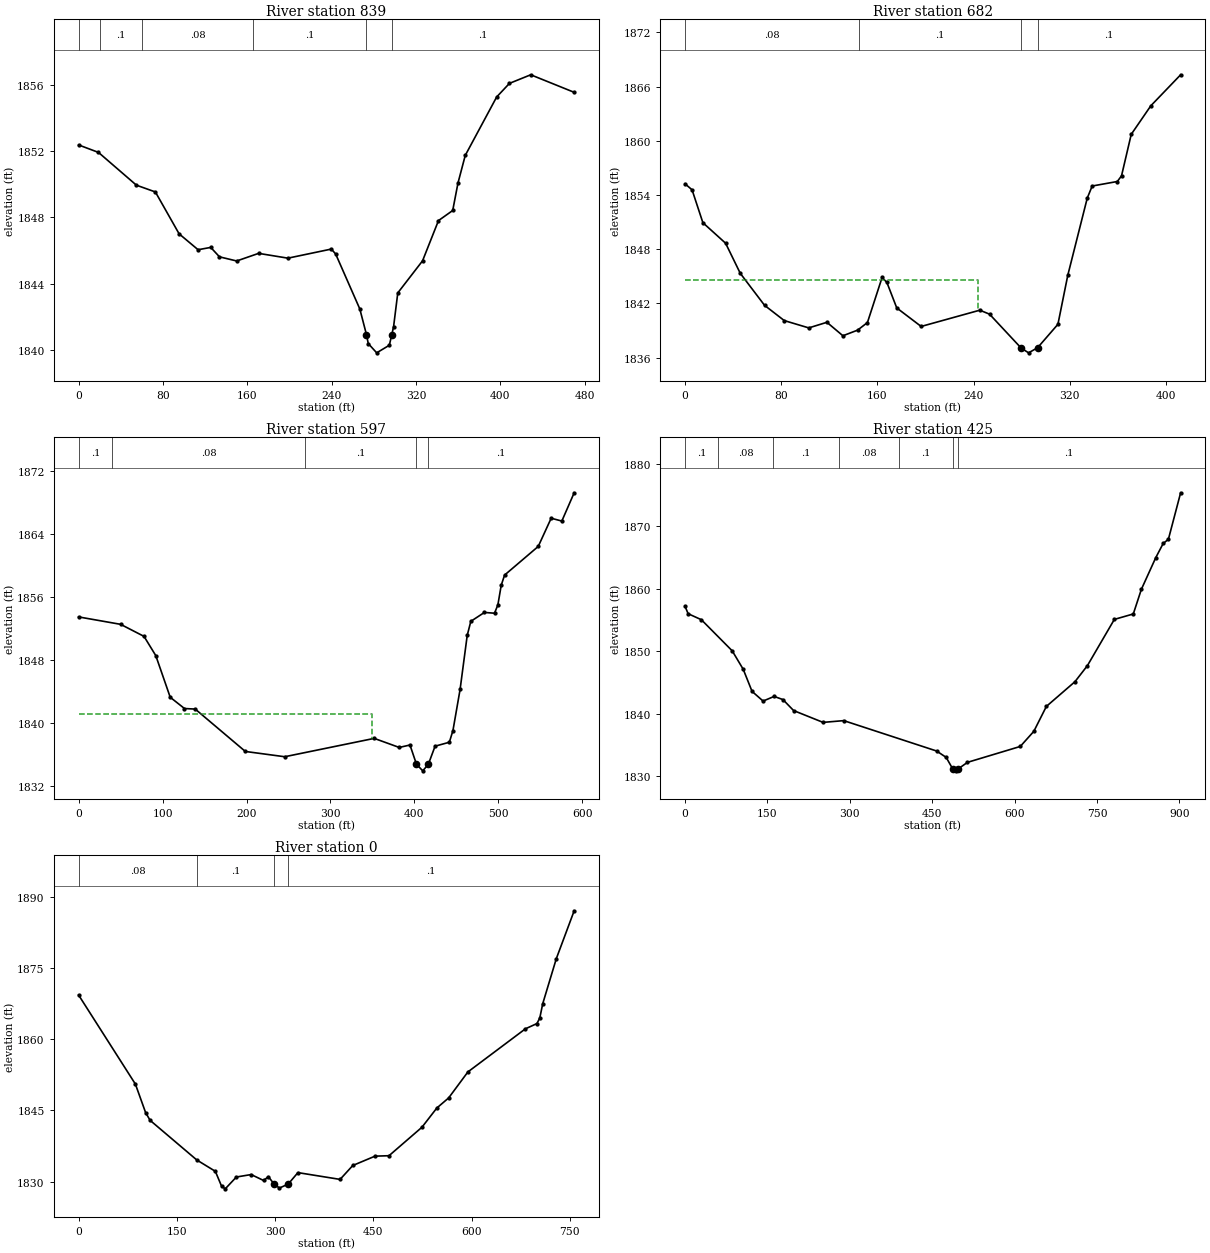
Type RM Length L Ch R = 1 ,839     ,151.7,156.4,155.4
XS GIS Cut Line= 5
2170009.37239203648436.5124479792170066.94416895648547.846954406
2170070.76498909648740.7983717952170022.04953223648776.140958148
2169931.30505375648787.603418587
#Sta/Elev= 30
       0 1852.38    18.8 1851.93    54.8 1849.95    72.8 1849.54    95.3 1847.01
   113.3 1846.05   125.3 1846.19   133.6 1845.62   149.9 1845.37   170.7 1845.83
   198.5 1845.54   239.7 1846.09   243.8 1845.79   266.7 1842.47     273 1840.92
   274.7 1840.38   282.7 1839.82   294.7 1840.28   296.9 1840.89   298.7 1841.39
   302.7 1843.44   326.2 1845.38   341.3 1847.81   354.8 1848.42   359.8 1850.08
   366.7 1851.75   396.5 1855.28   408.6  1856.1   428.8 1856.62     470 1855.56
#Mann= 6 ,-1,0
       0     .08       0      20      .1       0      60     .08       0
  165.34      .1       0     273    .045       0   296.9      .1       0
Bank Sta=273,296.9
XS Rating Curve= 0 ,0
Exp/Cntr(USF)=0,0
Exp/Cntr=0.3,0.1

Type RM Length L Ch R = 1 ,682     ,82.6,85.3,86.4
XS GIS Cut Line= 3
2170000.52669105648448.6868180312169989.63704909648458.215254744
2169918.17377374648849.561762631
#Sta/Elev= 30
       0 1855.23     5.8 1854.57    14.8 1850.93    33.7 1848.66    45.9 1845.33
    66.1 1841.79    82.5  1840.1   102.9 1839.29     118 1839.91   131.3 1838.42
   143.5 1839.04   151.7 1839.88   163.9 1844.87   167.9 1844.32   176.1  1841.5
   196.4 1839.45   245.2 1841.25   253.3 1840.81   279.6 1837.06   285.8 1836.53
   293.3  1837.1   310.2 1839.69   318.4 1845.11   334.6 1853.65   338.7 1854.99
   359.6 1855.49   363.1 1856.11   371.2 1860.71   387.5 1863.87   412.3  1867.3
#Mann= 4 ,-1,0
       0     .08       0  144.47      .1       0   279.6    .045       0
   293.3      .1       0
#XS Ineff= 2 , 0
          243.66 1844.63
Permanent Ineff=
       F       F
Bank Sta=279.6,293.3
XS Rating Curve= 0 ,0
Exp/Cntr(USF)=0,0
Exp/Cntr=0.3,0.1

Type RM Length L Ch R = 1 ,597     ,171.5,172.5,171.9
XS GIS Cut Line= 4
2170051.16364603 648377.210645012169965.87076374648427.925331773
2169837.93144032648774.8598934862169845.99968594648895.883577804
#Sta/Elev= 30
       0  1853.5      50 1852.56    77.9 1851.03    91.9 1848.59   109.1  1843.3
   126.1 1841.87   138.9  1841.8   198.6 1836.42   245.5 1835.75   352.1 1838.08
   381.9 1836.93   394.7 1837.24   402.4 1834.81   409.9 1833.96  416.58 1834.79
   424.6 1837.09   441.6 1837.59   445.9 1839.08   454.4 1844.29   462.9 1851.16
   467.2 1852.94   483.4 1854.07   495.4 1853.97   499.4 1855.02   503.4 1857.52
   507.4 1858.81   547.5 1862.45   562.9 1866.03   575.6 1865.67   590.3 1869.26
#Mann= 5 ,-1,0
       0      .1       0      40     .08       0  269.23      .1       0
   402.4    .045       0  416.58      .1       0
#XS Ineff= 2 , 0
          349.52 1841.18
Permanent Ineff=
       F       F
Bank Sta=402.4,416.58
XS Rating Curve= 0 ,0
Exp/Cntr(USF)=0,0
Exp/Cntr=0.3,0.1

Type RM Length L Ch R = 1 ,425     ,424.6,424.6,424.6
XS GIS Cut Line= 4
2170069.66103942648305.1719471392169860.60727389 648322.73949046
2169686.68859501648754.9010561672169818.44516992648939.360261042
#Sta/Elev= 30
       0 1857.15     5.5 1855.99    29.6 1855.03    85.8 1850.05   105.9 1847.09
   121.9 1843.57     142 1842.02   162.1 1842.76   178.1 1842.26   197.6  1840.5
   251.2 1838.61   288.9 1838.89     458 1834.03   475.4 1833.01   487.6 1831.12
   492.7 1830.86   496.81831.146   514.2 1832.22   610.3 1834.76     635 1837.18
   657.8 1841.16   709.9 1845.12   732.5 1847.68   781.6 1855.08   816.1 1855.95
   830.8 1859.89   857.1 1864.97   870.5 1867.22     880 1867.89   902.3 1875.33
#Mann= 7 ,-1,0
       0      .1       0      60     .08       0     160      .1       0
  279.79     .08       0  389.79      .1       0   487.6    .045       0
   496.8      .1       0
Bank Sta=487.6,496.8
XS Rating Curve= 0 ,0
Exp/Cntr(USF)=0,0
Exp/Cntr=0.3,0.1

Type RM Length L Ch R = 1 ,0       ,586.5,582.8,538.5
XS GIS Cut Line= 3
2169206.72148351648565.9536827492169526.08827728648883.554604708
2169798.89107107649023.075135155
#Sta/Elev= 30
       0 1869.31    86.7 1850.55   102.3 1844.54   109.2 1842.91   180.4 1834.57
   208.8 1832.17   218.3 1829.04   223.9 1828.48   240.9 1830.97   263.5 1831.49
   282.5 1830.24   289.8 1831.05  298.541829.482   306.7 1828.65   320.1 1829.49
   334.9  1831.9   399.3 1830.47   418.7  1833.4   452.7 1835.37     474 1835.46
   524.3 1841.46   547.1 1845.52   565.1 1847.64   594.5 1853.12   682.4 1862.21
   699.9 1863.31   704.3 1864.49   708.8 1867.51   729.6 1877.02   756.8 1887.08
#Mann= 4 ,-1,0
       0     .08       0   180.4      .1       0  298.54    .045       0
   320.1      .1       0
Bank Sta=298.54,320.1
XS Rating Curve= 0 ,0
Exp/Cntr=0.3,0.1
LCMann Table=0

Chan Stop Cuts=-1
Use User Specified Reach Order=0
Composite Channel Slope=5